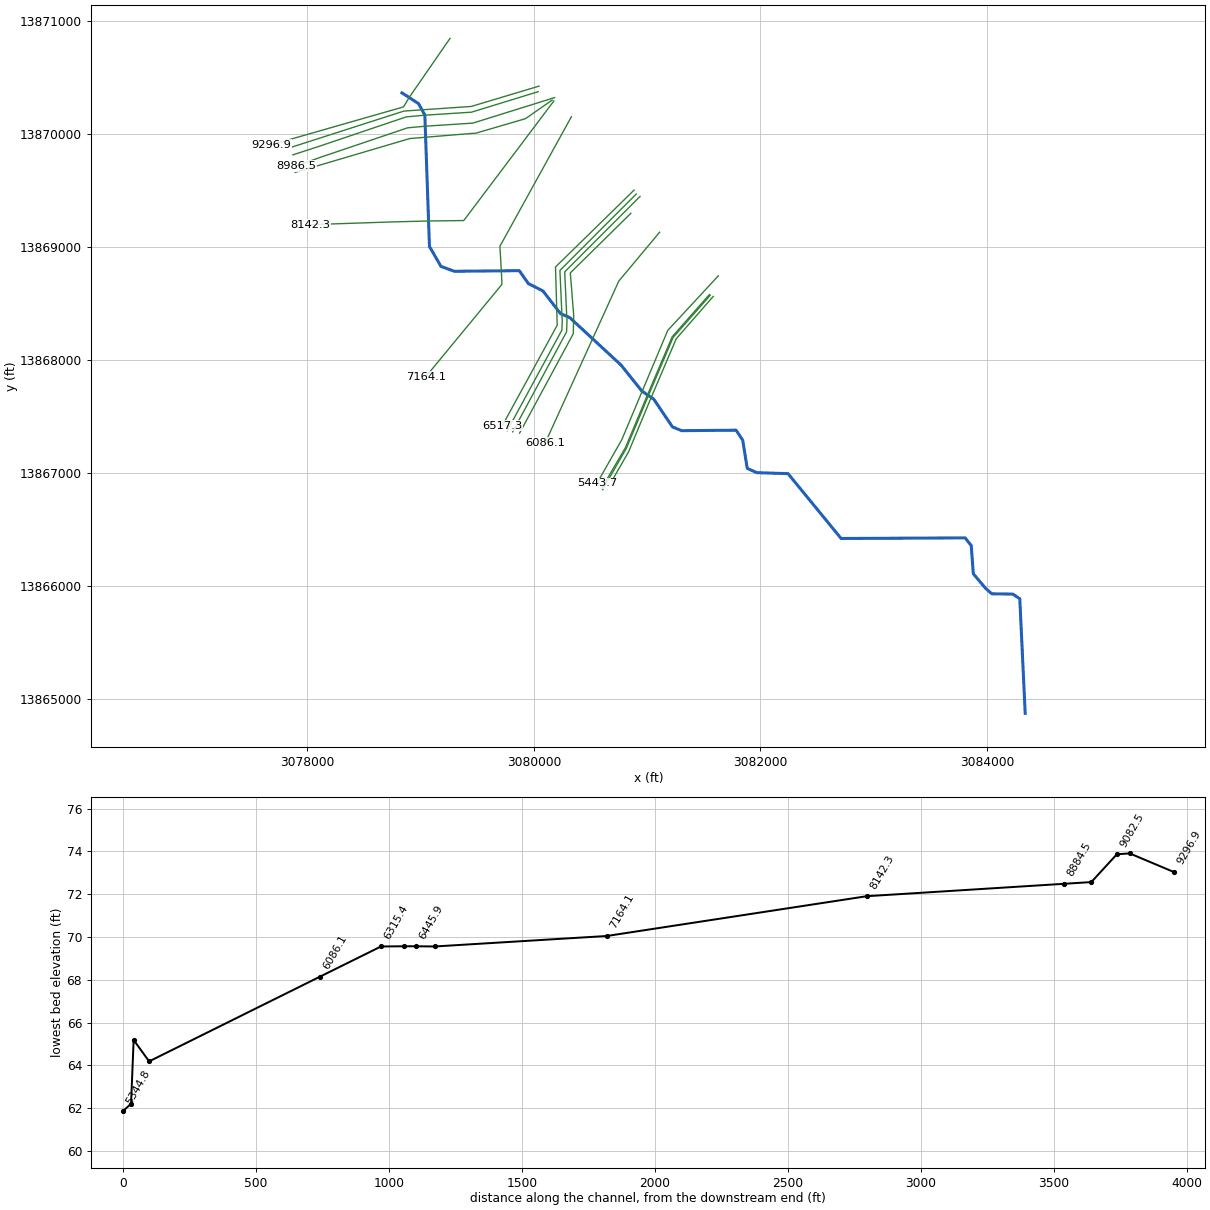
--- E115-04-00.prj (project) ---

Proj Title=E115-04-00
Current Plan=p02
Default Exp/Contr=.3,.1
English Units
Geom File=g01
Flow File=f02
Flow File=f01
Flow File=f04
Plan File=p01
Plan File=p04
Plan File=p02
Y Axis Title=Elevation
X Axis Title(PF)=Main Channel Distance
X Axis Title(XS)=Station
BEGIN DESCRIPTION:
White Oak Bayou Watershed
Brickhouse Gully Trib 1.61
HCFCD Unit E115-04-00
Flood Hazard Model
10, 2, 1, 0.2%
Filename E115-04-00
Prepared by:  Sabine Borgnet-Harris  DATE:  March 10, 2004
Reviewed by:  _____________________  DATE:  __________________
STATUS (Final)
END DESCRIPTION:
DSS File=dss
DSS Export Rating Curves= 0
DSS Export Rating Curve Sorted= 0
DSS Export Volume Flow Curves= 0
DXF OffsetX= 0
DXF OffsetY= 0
DXF ScaleX= 1
DXF ScaleY= 10

--- E115-04-00.p02 (plan) ---

Plan Title=Floodway
Version=Version 3.0.1  Mar 2001
Short Identifier=Floodway0607
Geom File=g01
Flow File=f02
Subcritical Flow
K Sum by GR= 0
Std Step Tol= 0.01
Critical Tol= 0.01
Num of Std Step Trials= 20
Max Error Tol= 0.3
Flow Tol Ratio= 0.001
Split Flow NTrial= 30
Split Flow Tol= 0.02
Split Flow Ratio= 0.02
Log Output Level= 0
Friction Slope Method= 1
Unsteady Friction Slope Method= 2
Parabolic Critical Depth
Global Vel Dist= 0 , 0 , 0
Global Log Level= 0
CheckData=True
Encroach Param=-1 ,0,0, 5
Encroach River=E115-04-00
Encroach Reach=Reach - 1
Encroach Node=9296.9
       1    4890    5110       4       1               4      .8
       4      .6
Encroach Node=9130.8
       1    4880    5120       0       0       0       0       0       0
       0       0       0
Encroach Node=9082.5
       1    4880    5120       4       1               4      .8
       4      .6
Encroach Node=9034.5
       1    4880    5120       4       1               4      .8
       4      .6
Encroach Node=8986.5
       1    4880    5120       4       1               4      .8
       4      .6
Encroach Node=8884.5
       1    4955    5110       0       0       0       0       0       0
       0       0       0
Encroach Node=8142.3
       1  4965.2    5110       4       1               4      .8
       4      .6
Encroach Node=7164.1
       1    4935    5200       4       1               4      .8
       4      .6
Encroach Node=6517.3
       1    4950    5200       0       0       0       0       0       0
       0       0       0
Encroach Node=6445.9
       1    3650    3900       4       1               4      .8
       4      .6
Encroach Node=6423.4
       1    3650    3900       4       1               4      .8
       4      .6
Encroach Node=6400.9
       1    3650    3900       4       1               4      .8
       4      .6
Encroach Node=6315.4
       1    4955    5120       0       0       0       0       0       0
       0       0       0
Encroach Node=6086.1
       1    4971    5150       0       0       0       0       0       0
       0       0       0
Encroach Node=5443.7
       1    4850    5150       0       0       0       0       0       0
       0       0       0
Encroach Node=5385.5
       1    4850    5150       0       0       0       0       0       0
       0       0       0
Encroach Node=5375.7
       1    4850    5150       0       0       0       0       0       0
       0       0       0
Encroach Node=5344.8
       1    4850    5150       4       1               4      .8
       4      .6
Encroach Node=5280.8
       1    4850    5150       4       1               4      .8
       4      .6
Encroach Node=5216.8
       1    4850    5150       4       1               4      .8
       4      .6
Encroach Node=5200.3
       1    4760    5060       0       0       0       0       0       0
       0       0       0
Encroach Node=5076.5
       1    4760    5060       0       0       0       0       0       0
       0       0       0
Encroach Node=4964.4
       1    4760    5060       0       0       0       0       0       0
       0       0       0
Encroach Node=4811.1
       1    4760    5060       4       1               4      .8
       4      .6
Encroach Node=4752.8
       1    4760    5060       4       1               4      .8
       4      .6
Encroach Node=4692.8
       1    4760    5060       4       1               4      .8
       4      .6
Encroach Node=4632.8
       1    4760    5060       4       1               4      .8
       4      .6
Encroach Node=4611.6
       1    4760    5030       4       1               4      .8
       4      .6
Encroach Node=4449.0
       1    4830    5090       0       0       0       0       0       0
       0       0       0
Encroach Node=4333.8
       1    4770    5120       4       1               4      .8
       4      .6
Encroach Node=4273.1
       1    4710    5120       4       1               4      .8
       4      .6
Encroach Node=4213.1
       1    4710    5120       4       1               4      .8
       4      .6
Encroach Node=4153.1
       1    4710    5120       4       1               4      .8
       4      .6
Encroach Node=4104.3
       1    4710    5120       0       0       0       0       0       0
       0       0       0
Encroach Node=3999.4
       1    4710    5100       0       0       0       0       0       0
       0       0       0
Encroach Node=3960.5
       1    4710    5130       4       1               4      .8
       4      .6
Encroach Node=3925.5
       1    4710    5130       4       1               4      .8
       4      .6
Encroach Node=3890.5
       1    4710    5130       4       1               4      .8
       4      .6
Encroach Node=3830.6
       1    4710    5080       0       0       0       0       0       0
       0       0       0
Encroach Node=3255.3
       1    4710    5075       4       1               4      .8
       4      .6
Encroach Node=2039.4
       1  4967.8    5066       4       1               4      .8
       4      .6
Encroach Node=1367.1
       1    4865    5150       0       0       0       0       0       0
       0       0       0
Encroach Node=1309.6
       1    4865    5150       4       1               4      .8
       4      .6
Encroach Node=1283.1
       1    4865    5150       4       1               4      .8
       4      .6
Encroach Node=1256.6
       1    4865    5150       4       1               4      .8
       4      .6
Encroach Node=1211.6
       1    4865    5150       0       0       0       0       0       0
       0       0       0
Encroach Node=224.0
       1  4965.9  5029.6       4       1               4      .8
       4      .6
Encroach Reach=E115-04-00_0002
Encroach Node=9296.9
       1    4890    5110       0       0       0       0       0       0
       0       0       0
Encroach Node=9130.8
       1    4880    5120       0       0       0       0       0       0
       0       0       0
Encroach Node=9082.5
       1    4880    5120       0       0       0       0       0       0
       0       0       0
Encroach Node=9034.5
       1    4880    5120       0       0       0       0       0       0
       0       0       0
Encroach Node=8986.5
       1    4880    5120       0       0       0       0       0       0
       0       0       0
Encroach Node=8884.5
       1    4955    5110       0       0       0       0       0       0
       0       0       0
Encroach Node=8142.3
       1  4965.2    5110       0       0       0       0       0       0
       0       0       0
Encroach Node=7164.1
       1    4935    5200       0       0       0       0       0       0
       0       0       0
Encroach Node=6517.3
       1    4950    5200       0       0       0       0       0       0
       0       0       0
Encroach Node=6445.9
       1    3650    3900       0       0       0       0       0       0
       0       0       0
Encroach Node=6423.4
       1    3650    3900       0       0       0       0       0       0
       0       0       0
Encroach Node=6400.9
       1    3650    3900       0       0       0       0       0       0
       0       0       0
Encroach Node=6315.4
       1    4955    5120       0       0       0       0       0       0
       0       0       0
Encroach Node=6086.1
       1    4971    5150       0       0       0       0       0       0
       0       0       0
Encroach Node=5443.7
       1    4850    5150       0       0       0       0       0       0
       0       0       0
Encroach Node=5385.5
       1    4850    5150       0       0       0       0       0       0
       0       0       0
Encroach Node=5375.7
       1    4850    5150       0       0       0       0       0       0
       0       0       0
Encroach Node=5344.8
       1    4850    5150       0       0       0       0       0       0
       0       0       0
Encroach Node=5280.8
       1    4850    5150       0       0       0       0       0       0
       0       0       0
Encroach Node=5216.8
       1    4850    5150       0       0       0       0       0       0
       0       0       0
Encroach Node=5200.3
       1    4760    5060       0       0       0       0       0       0
       0       0       0
Encroach Node=5076.5
       1    4760    5060       0       0       0       0       0       0
       0       0       0
Encroach Node=4964.4
       1    4760    5060       0       0       0       0       0       0
       0       0       0
Encroach Node=4811.1
       1    4760    5060       0       0       0       0       0       0
       0       0       0
Encroach Node=4752.8
       1    4760    5060       0       0       0       0       0       0
       0       0       0
Encroach Node=4692.8
       1    4760    5060       0       0       0       0       0       0
       0       0       0
Encroach Node=4632.8
       1    4760    5060       0       0       0       0       0       0
       0       0       0
Encroach Node=4611.6
       1    4760    5030       0       0       0       0       0       0
       0       0       0
Encroach Node=4449.0
       1    4830    5090       0       0       0       0       0       0
       0       0       0
Encroach Node=4333.8
       1    4770    5120       0       0       0       0       0       0
       0       0       0
Encroach Node=4273.1
       1    4710    5120       0       0       0       0       0       0
       0       0       0
Encroach Node=4213.1
       1    4710    5120       0       0       0       0       0       0
       0       0       0
Encroach Node=4153.1
       1    4710    5120       0       0       0       0       0       0
       0       0       0
Encroach Node=4104.3
       1    4710    5120       0       0       0       0       0       0
       0       0       0
Encroach Node=3999.4
       1    4710    5100       0       0       0       0       0       0
       0       0       0
Encroach Node=3960.5
       1    4710    5130       0       0       0       0       0       0
       0       0       0
Encroach Node=3925.5
       1    4710    5130       0       0       0       0       0       0
       0       0       0
Encroach Node=3890.5
       1    4710    5130       0       0       0       0       0       0
       0       0       0
Encroach Node=3830.6
       1    4710    5080       0       0       0       0       0       0
       0       0       0
Encroach Node=3255.3
       1    4710    5075       0       0       0       0       0       0
       0       0       0
Encroach Node=2039.4
       1  4967.8    5066       0       0       0       0       0       0
       0       0       0
Encroach Node=1367.1
       1    4865    5150       0       0       0       0       0       0
       0       0       0
Encroach Node=1309.6
       1    4865    5150       0       0       0       0       0       0
       0       0       0
Encroach Node=1283.1
       1    4865    5150       0       0       0       0       0       0
       0       0       0
Encroach Node=1256.6
       1    4865    5150       0       0       0       0       0       0
       0       0       0
Encroach Node=1211.6
       1    4865    5150       0       0       0       0       0       0
       0       0       0
Encroach Node=224.0
       1  4965.9  5029.6       0       0       0       0       0       0
       0       0       0
Computation Interval=1HOUR
Output Interval=1HOUR
Run HTab= 0
Run UNet= 0
Run PostProcess= 0
UNET Theta= 1
UNET ZTol= 0.02
UNET ZSATol= 0.1
UNET MxIter= 20
UNET MaxInSteps= 20
UNET DtIC= 0
UNET DtMin= 0
UNET MaxCRTS= 20
UNET WFStab= 2
UNET SFStab= 1
UNET WFX= 1
UNET SFX= 1
UNET Convert EG Bridges=-1
UNET Use Existing IB Tables=-1
Instantaneous Interval=1HOUR
DSS File=dss
Write IC File= 0
IC Time=0
Write Velocity= 0
Write Detailed= 0

--- E115-04-00.p01 (plan) ---

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Plan Title=FEMA Effective June 2007
Short Identifier=FEMAeff0607
Geom File=g01
Flow File=f01
Encroach Param=-1 ,0,0, 2

--- E115-04-00.p04 (plan) ---

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Plan Title=Storage Routing
Program Version=3.13
Short Identifier=Store_Rout
Geom File=g01
Flow File=f04
Unsteady Bridges Friction Slope Method= 1
Encroach Param=-1 ,0,0, 0
UNET Theta Warmup= 1
UNET DSS MLevel= 4
UNET DZMax Abort= 100
UNET Froude Reduction=False
UNET Froude Limit= 1
UNET Froude Power= 10
Echo Input=False
Echo Output=False
Detailed Automatic Start=False, 10

--- E115-04-00.f02 (steady flow) ---

Flow Title=Floodway
Version=Version 3.0.1  Mar 2001
Number of Profiles= 2
Profile Names=1PCT_100yr, 1PCTFloodway_100yrFW
River Rch & RM=E115-04-00,E115-04-00_0002       ,9296.9
    1230    1230
River Rch & RM=E115-04-00,E115-04-00_0002       ,9082.5
    1390    1390
River Rch & RM=E115-04-00,E115-04-00_0002       ,8142.3
    1580    1580
River Rch & RM=E115-04-00,E115-04-00_0002       ,7164.1
    1740    1740
River Rch & RM=E115-04-00,E115-04-00_0002       ,6445.9
    1990    1990
River Rch & RM=E115-04-00,E115-04-00_0002       ,5385.5
    2000    2000
River Rch & RM=E115-04-00,E115-04-00_0002       ,5344.8
    2150    2150
River Rch & RM=E115-04-00,E115-04-00_0002       ,4811.1
    2180    2180
River Rch & RM=E115-04-00,E115-04-00_0002       ,4752.8
    2300    2300
River Rch & RM=E115-04-00,E115-04-00_0002       ,4273.1
    2320    2320
River Rch & RM=E115-04-00,E115-04-00_0002       ,3960.5
    2350    2350
River Rch & RM=E115-04-00,E115-04-00_0002       ,3255.3
    2400    2400
River Rch & RM=E115-04-00,E115-04-00_0002       ,2039.4
    2440    2440
River Rch & RM=E115-04-00,E115-04-00_0002       ,1309.6
    2500    2500
Boundary for River Rch & Prof#=E115-04-00,E115-04-00_0002       , 1
Up Type= 0
Dn Type= 3
Dn Slope=.002
Boundary for River Rch & Prof#=E115-04-00,E115-04-00_0002       , 2
Up Type= 0
Dn Type= 1
Dn Known WS=70.31
DSS Import GetInterval= 0
DSS Import GetPeak= 0
DSS Import FillOption= 0

--- E115-04-00.f01 (steady flow) ---

Flow Title=FEMA Effective June 2007
Version=Version 3.0.1  Mar 2001
Number of Profiles= 4
Profile Names=10PCT_10yr, 2PCT_50yr, 1PCT_100yr, 0.2PCT_500yr
River Rch & RM=E115-04-00,E115-04-00_0002       ,9296.9
     690    1020    1230    1750
River Rch & RM=E115-04-00,E115-04-00_0002       ,9082.5
     790    1160    1390    1980
River Rch & RM=E115-04-00,E115-04-00_0002       ,8142.3
     920    1330    1580    2250
River Rch & RM=E115-04-00,E115-04-00_0002       ,7164.1
    1020    1480    1740    2490
River Rch & RM=E115-04-00,E115-04-00_0002       ,6445.9
    1190    1710    1990    2850
River Rch & RM=E115-04-00,E115-04-00_0002       ,5385.5
    1200    1720    2000    2860
River Rch & RM=E115-04-00,E115-04-00_0002       ,5344.8
    1290    1850    2150    3070
River Rch & RM=E115-04-00,E115-04-00_0002       ,4811.1
    1320    1890    2180    3120
River Rch & RM=E115-04-00,E115-04-00_0002       ,4752.8
    1400    2000    2300    3300
River Rch & RM=E115-04-00,E115-04-00_0002       ,4273.1
    1410    2010    2320    3320
River Rch & RM=E115-04-00,E115-04-00_0002       ,3960.5
    1420    2020    2350    3350
River Rch & RM=E115-04-00,E115-04-00_0002       ,3255.3
    1450    2050    2400    3400
River Rch & RM=E115-04-00,E115-04-00_0002       ,2039.4
    1470    2070    2440    3440
River Rch & RM=E115-04-00,E115-04-00_0002       ,1309.6
    1500    2100    2500    3500
Boundary for River Rch & Prof#=E115-04-00,E115-04-00_0002       , 1
Up Type= 0
Dn Type= 3
Dn Slope=.002
Boundary for River Rch & Prof#=E115-04-00,E115-04-00_0002       , 2
Up Type= 0
Dn Type= 3
Dn Slope=.002
Boundary for River Rch & Prof#=E115-04-00,E115-04-00_0002       , 3
Up Type= 0
Dn Type= 3
Dn Slope=.002
Boundary for River Rch & Prof#=E115-04-00,E115-04-00_0002       , 4
Up Type= 0
Dn Type= 3
Dn Slope=.002
DSS Import GetInterval= 0
DSS Import GetPeak= 0
DSS Import FillOption= 0

--- E115-04-00.f04 (steady flow) ---

Flow Title=Storage Routing
Version=Version 3.0.1  Mar 2001
Number of Profiles= 7
Profile Names=.25x10% flood,.50x10% flood,10% flood,2% flood,1% flood,0.2% flood,1.25x0.2% flood
River Rch & RM=E115-04-00,E115-04-00_0002       ,9296.9
     130     260     510     710     800    1110    1390
River Rch & RM=E115-04-00,E115-04-00_0002       ,9034.5
     170     330     664     930    1050    1460    1830
River Rch & RM=E115-04-00,E115-04-00_0002       ,6445.9
     190     370     744    1042    1235    1719    2150
River Rch & RM=E115-04-00,E115-04-00_0002       ,4752.8
     220     430     850    1190    1480    2060    2580
River Rch & RM=E115-04-00,E115-04-00_0002       ,3941.3
     250     490     980    1380    1570    2180    2730
Boundary for River Rch & Prof#=E115-04-00,E115-04-00_0002       , 1
Up Type= 0
Dn Type= 3
Dn Slope=.002
Boundary for River Rch & Prof#=E115-04-00,E115-04-00_0002       , 2
Up Type= 0
Dn Type= 3
Dn Slope=.002
Boundary for River Rch & Prof#=E115-04-00,E115-04-00_0002       , 3
Up Type= 0
Dn Type= 3
Dn Slope=.002
Boundary for River Rch & Prof#=E115-04-00,E115-04-00_0002       , 4
Up Type= 0
Dn Type= 3
Dn Slope=.002
Boundary for River Rch & Prof#=E115-04-00,E115-04-00_0002       , 5
Up Type= 0
Dn Type= 3
Dn Slope=.002
Boundary for River Rch & Prof#=E115-04-00,E115-04-00_0002       , 6
Up Type= 0
Dn Type= 3
Dn Slope=.002
Boundary for River Rch & Prof#=E115-04-00,E115-04-00_0002       , 7
Up Type= 0
Dn Type= 3
Dn Slope=.002
DSS Import GetInterval= 0
DSS Import GetPeak= 0
DSS Import FillOption= 0

--- E115-04-00.g01 (geometry) ---

Geom Title=E115-04-00 June 2007
Program Version=3.13

River Reach=E115-04-00      ,E115-04-00_0002
Reach XY= 30
      3078834.46     13870362.27      3078980.92      13870266.9
      3079036.47      13870166.2      3079077.27     13869003.01
      3079178.83     13868826.79      3079296.02     13868783.39
      3079870.67      13868788.6      3079950.53     13868674.88
      3080079.87     13868608.91      3080234.21     13868409.01
      3080315.98     13868373.67      3080769.98     13867952.66
      3080952.27     13867724.36      3081059.04     13867650.58
       3081223.1     13867406.65      3081303.83      13867372.8
      3081784.73     13867377.14      3081843.76      13867288.6
      3081883.69     13867039.47      3081967.03     13867001.27
      3082243.94     13866992.59      3082712.69     13866418.81
      3083808.17     13866424.01      3083861.99     13866356.31
      3083880.22     13866106.31       3083989.6     13865976.97
      3084043.41     13865929.22      3084230.05     13865926.62
      3084290.81     13865884.95      3084338.55       13864871.

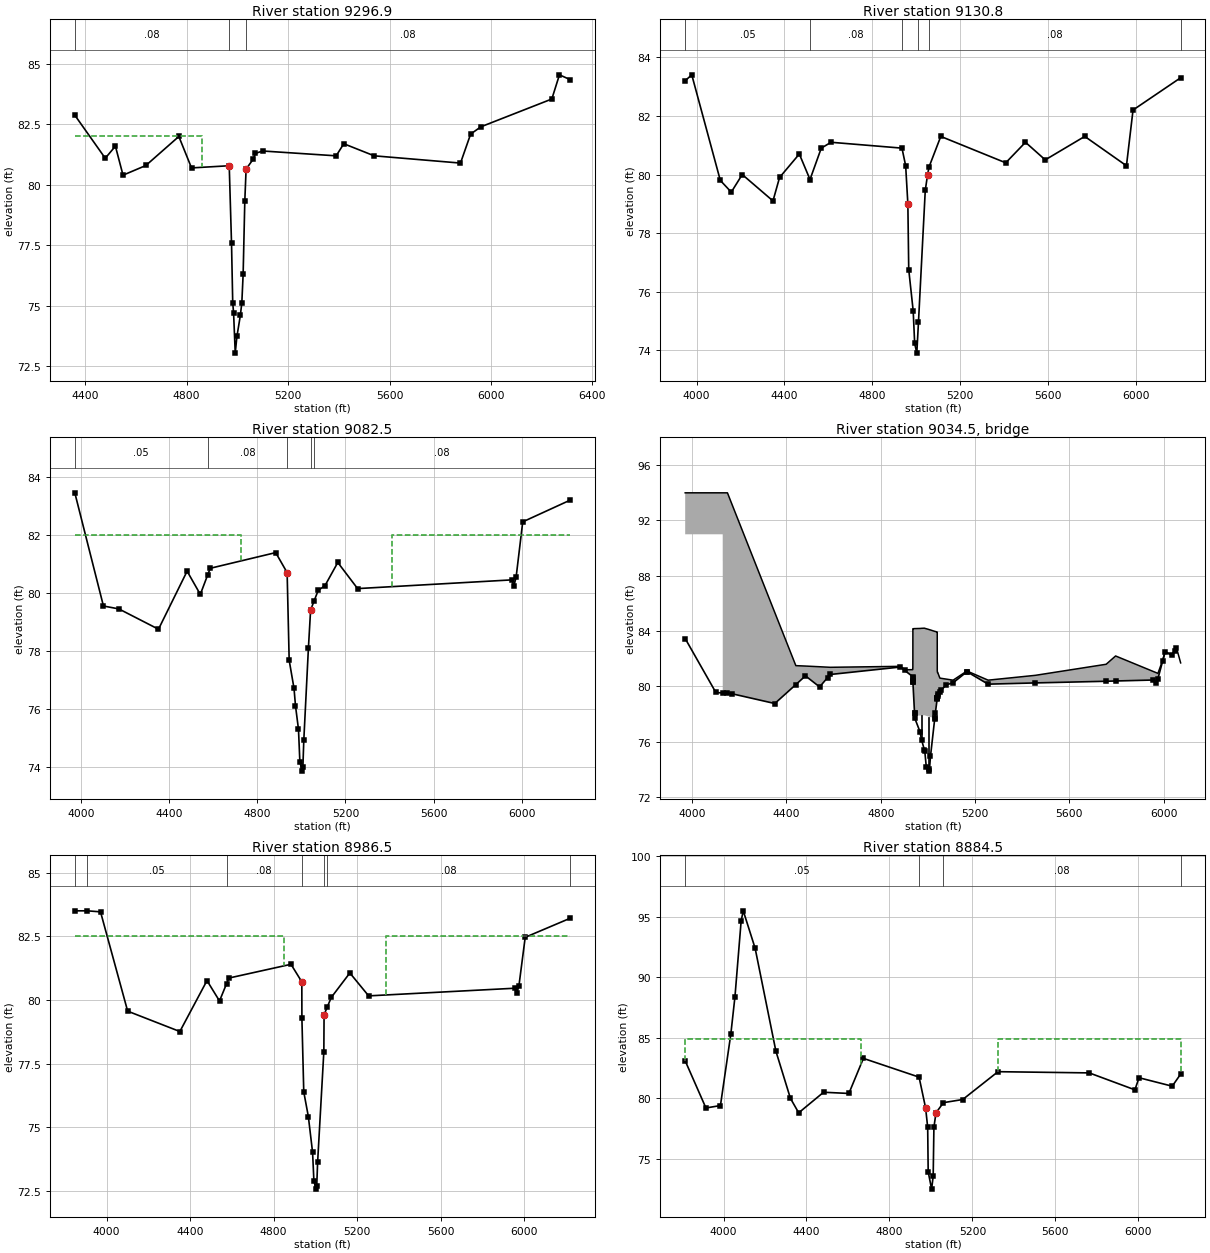
Type RM Length L Ch R = 1 ,9296.9  ,316.3,166.1,47.2
BEGIN DESCRIPTION:
Cross Section X07
Located At: US PINEMONT
END DESCRIPTION:
XS GIS Cut Line= 5
      3079259.14     13870844.84      3078939.53     13870381.42
      3078898.73     13870322.08      3078848.04     13870238.01
      3077682.33      13869903.6
#Sta/Elev= 30
  4359.7   82.88  4479.7    81.1  4519.7    81.6  4549.7    80.4  4639.7    80.8
  4769.7      82  4819.7    80.7  4968.3   80.79  4977.3    77.6  4982.1   75.12
  4985.5    74.7    4992   73.04  4998.6   73.73  5012.3   74.61    5018   75.13
  5023.1    76.3  5029.7   79.33  5034.8   80.65  5062.6   81.06  5071.6    81.3
  5099.8    81.4  5389.8    81.2  5419.8    81.7  5539.8    81.2  5879.8    80.9
  5919.8    82.1  5960.1    82.4  6239.8   83.55  6269.8   84.55  6312.5   84.35
#Mann= 3 ,-1 , 0
  4359.7     .08       0  4968.3     .04       0  5034.8     .08       0
#XS Ineff= 2 , 0
       0    4860      82               0
Permanent Ineff=
       T       F
Bank Sta=4968.3,5034.8
Exp/Cntr=0.3,0.1

Type RM Length L Ch R = 1 ,9130.8  ,48.2,48.3,58.5
BEGIN DESCRIPTION:
Cross Section BR 6-US
END DESCRIPTION:
XS GIS Cut Line= 4
      3080044.61      13870421.7      3079446.41      13870242.2
      3078851.96      13870201.1      3077864.93      13869883.3
#Sta/Elev= 30
    3948    83.2    3978    83.4    4108    79.8    4158    79.4    4208      80
    4348    79.1    4378    79.9    4468    80.7  4516.7   79.83    4568    80.9
  4612.5    81.1  4935.7    80.9  4952.5    80.3  4962.5      79  4966.5   76.76
  4986.8   75.35  4993.5   74.24  5003.3   73.91  5010.9   74.97  5041.8   79.46
  5052.5      80  5059.1   80.26  5112.5    81.3  5408.4    80.4  5498.4    81.1
  5588.4    80.5  5768.4    81.3  5958.4    80.3  5988.4    82.2  6205.3    83.3
#Mann= 6 ,-1 , 0
    3948     .05       0  4516.7     .08       0  4935.7     .04       0
  5010.9     .04       0  5059.1     .08       0  6205.3      .2       0
Bank Sta=4962.5,5052.5
Exp/Cntr=0.5,0.3

Type RM Length L Ch R = 1 ,9082.5  ,94.9,96,115.9
BEGIN DESCRIPTION:
Upstream Section of Bridge/Culvert/Weir
END DESCRIPTION:
XS GIS Cut Line= 6
      3080037.53      13870372.8      3079449.33     13870191.48
      3079037.61     13870164.73      3078871.69     13870149.52
      3078113.81     13869892.86      3077870.99     13869813.68
#Sta/Elev= 30
  3970.9   83.46  4100.9   79.56  4170.9   79.46  4350.9   78.76  4480.9   80.76
  4540.9   79.96  4574.8   80.64  4586.1   80.86  4883.3    81.4  4935.2   80.71
  4944.5   77.69  4966.5   76.72  4973.2   76.12  4986.8   75.31    4993    74.2
  5003.3   73.87  5006.7      74  5010.9   74.93  5031.8    78.1  5041.8   79.42
  5057.4   79.73  5076.4    80.1    5107   80.26  5165.3   81.06  5255.3   80.16
  5955.3   80.46  5965.3   80.26  5975.3   80.56  6005.3   82.46  6221.2   83.21
#Mann= 5 ,-1 , 0
  3970.9     .05       0  4574.8     .08       0  4935.2     .04       0
  5041.8     .04       0  5057.4     .08       0
#XS Ineff= 2 , 0
       0    4725      82    5410       0      82
Permanent Ineff=
       T       T
Bank Sta=4935.2,5041.8
Exp/Cntr=0.5,0.3

Type RM Length L Ch R = 3 ,9034.5  ,,,
BEGIN DESCRIPTION:
PINEMONT DRIVE
Structure ID: E115-04-00-06
END DESCRIPTION:
Bridge Culvert--1,0,-1,-1, 0
Deck Dist Width WeirC Skew NumUp NumDn MinLoCord MaxHiCord MaxSubmerge Is_Ogee
10,76,2.6,0, 59, 59, , , 0.95, 0, ,,,
  3970.9  4100.9  4130.1  4130.2  4150.1  4170.9  4350.9  4440.1  4480.9  4540.9
  4574.8  4586.1  4883.3  4901.9  4935.2  4935.6 4936.19  4936.3 4936.41 4943.21
  4943.3  4944.5  4966.5  4973.2    4985  4986.8    4993  5003.3  5006.7  5010.9
 5028.99  5029.1  5031.8 5039.49  5039.6 5039.71    5040  5040.7  5041.8  5050.7
  5057.4  5076.4    5107  5165.3  5165.8  5255.3  5455.8  5755.8  5795.8  5955.3
  5965.3  5975.3  5995.8  6005.3  6035.3  6045.8  6053.5  6065.8  6071.6
      94      94      94      94      94    93.1   85.34    81.5   81.47   81.42
   81.39   81.38   81.45    81.2   81.21   81.21   81.37   84.17   84.17   84.18
   84.18   84.18   84.19    84.2   84.21    84.2   84.17   84.12    84.1   84.08
   83.98   83.98   83.97   83.93   83.93   81.13   81.08      81      81    80.6
   80.58   80.53   80.45   81.11   81.11   80.45    80.8    81.6    82.2   81.08
   81.01   80.94   81.91   82.51   82.31    82.6   82.81   82.06    81.7
      91      91      91      79   79.49   79.46   78.76   80.13   80.76   79.96
      70      70      70      70      70      70      70      70      70      70
      70   77.88   77.89    77.9   77.91    77.9   77.87   77.82    77.8   77.78
   77.71   77.71
                                                                                
                                                                        
  3970.9  4100.9  4130.1  4130.2  4150.1  4170.9  4350.9  4440.1  4480.9  4540.9
  4574.8  4586.1  4883.3  4901.9  4935.2  4935.6 4936.19  4936.3 4936.41 4943.21
  4943.3  4944.5  4966.5  4973.2    4985  4986.8    4993  5003.3  5006.7  5010.9
 5028.99  5029.1  5031.8 5039.49  5039.6 5039.71    5040  5040.7  5041.8  5050.7
  5057.4  5076.4    5107  5165.3  5165.8  5255.3  5455.8  5755.8  5795.8  5955.3
  5965.3  5975.3  5995.8  6005.3  6035.3  6045.8  6053.5  6065.8  6071.6
      94      94      94      94      94    93.1   85.34    81.5   81.47   81.42
   81.39   81.38   81.45    81.2   81.21   81.21   81.37   84.17   84.17   84.18
   84.18   84.18   84.19    84.2   84.21    84.2   84.17   84.12    84.1   84.08
   83.98   83.98   83.97   83.93   83.93   81.13   81.08      81      81    80.6
   80.58   80.53   80.45   81.11   81.11   80.45    80.8    81.6    82.2   81.08
   81.01   80.94   81.91   82.51   82.31    82.6   82.81   82.06    81.7
      91      91      91      79   79.49   79.46   78.76   80.13   80.76   79.96
                                                                                
           77.88   77.89    77.9   77.91    77.9   77.87   77.82    77.8   77.78
   77.71   77.71
                                                                                
                                                                        
Pier Skew, UpSta & Num, DnSta & Num=  ,4973.2, 2 ,4973.2, 2 , 0 , 0 , 0 ,,
     2.5     2.5
       0      80
     2.5     2.5
       0      80
Pier Skew, UpSta & Num, DnSta & Num=  ,5003.3, 2 ,5003.3, 2 , 0 , 0 , 0 ,,
     2.5     2.5
       0      80
     2.5     2.5
       0      80
BR Coef= 1 , 1 , 1 ,1.25, 0 ,,,0.8,0,2,0,
WSPro=,,,, 1 ,,,, 0 ,,,, 0 ,,,,-1 ,-1 ,-1 , 0 , 0 , 0 , 0 , 0
BR U #Sta/Elev= 56
  3970.9   83.46  4100.9   79.56  4130.1   79.52  4150.1   79.49  4170.9   79.46
  4350.9   78.76  4440.1   80.13  4480.9   80.76  4540.9   79.96  4574.8   80.64
  4586.1   80.86  4883.3    81.4  4901.9   81.15  4935.2   80.71  4935.6   80.58
 4936.19   80.39  4936.3   80.35 4936.41   80.32 4943.21   78.11  4943.3   78.08
  4944.5   77.69  4966.5   76.72  4973.2   76.12    4985   75.42  4986.8   75.31
    4993    74.2  5003.3   73.87  5006.7      74  5010.9   74.93 5028.99   77.67
  5029.1   77.69  5031.8    78.1 5039.49   79.12  5039.6   79.13 5039.71   79.14
    5040   79.18  5040.7   79.27  5041.8   79.42  5050.7   79.59  5057.4   79.73
  5076.4    80.1    5107   80.26  5165.3   81.06  5165.8   81.06  5255.3   80.16
  5455.8   80.25  5755.8   80.37  5795.8   80.39  5955.3   80.46  5965.3   80.26
  5975.3   80.56  5995.8   81.86  6005.3   82.46  6035.3   82.26  6045.8   82.55
  6053.5   82.76
BR U #Mann= 5
  3970.9     .05  4574.8     .08  4935.2     .04  5041.8     .04  5057.4     .08
BR D #Sta/Elev= 56
  3970.9   83.46  4100.9   79.56  4130.1   79.52  4150.1   79.49  4170.9   79.46
  4350.9   78.76  4440.1   80.13  4480.9   80.76  4540.9   79.96  4574.8   80.64
  4586.1   80.86  4883.3    81.4  4901.9   81.15  4935.2   80.71  4935.6   79.28
 4936.19   79.09  4936.3   79.05 4936.41   79.02 4943.21   76.81  4943.3   76.78
  4944.5   76.39  4966.5   75.42  4973.2   74.82    4985   74.12  4986.8   74.01
    4993    72.9  5003.3   72.57  5006.7    72.7  5010.9   73.63 5028.99   76.37
  5029.1   76.39  5031.8    76.8 5039.49   77.82  5039.6   77.83 5039.71   77.84
    5040   77.88  5040.7   77.97  5041.8   79.42  5050.7   79.59  5057.4   79.73
  5076.4    80.1    5107   80.26  5165.3   81.06  5165.8   81.06  5255.3   80.16
  5455.8   80.25  5755.8   80.37  5795.8   80.39  5955.3   80.46  5965.3   80.26
  5975.3   80.56  5995.8   81.86  6005.3   82.46  6035.3   82.26  6045.8   82.55
  6053.5   82.76
BR D #Mann= 5
  3970.9     .05  4574.8     .08  4935.2     .04  5041.8     .04  5057.4     .08
BC Design=,, 0 ,, 0 ,,,,,,
BC HTab HWMax=83.46

Type RM Length L Ch R = 1 ,8986.5  ,92.5,102,126.5
BEGIN DESCRIPTION:
Downstream Section of Bridge/Culvert/Weir
END DESCRIPTION:
XS GIS Cut Line= 6
       3080182.5      13870320.5      3079460.85     13870094.64
      3079043.83     13870067.55      3078884.44     13870052.93
      3078120.75     13869794.31       3077901.4     13869715.67
#Sta/Elev= 30
 3847.76    83.5  3907.6    83.5  3970.9   83.46  4100.9   79.56  4350.9   78.76
  4480.9   80.76  4540.9   79.96  4574.8   80.64  4586.1   80.86  4883.3    81.4
  4935.2   80.71  4935.6   79.28  4944.5   76.39  4966.5   75.42  4986.8   74.01
    4993    72.9  5003.3   72.57  5006.7    72.7  5010.9   73.63  5040.7   77.97
  5041.8   79.42  5057.4   79.73  5076.4    80.1  5165.3   81.06  5255.3   80.16
  5955.3   80.46  5965.3   80.26  5975.3   80.56  6005.3   82.46  6221.2   83.21
#Mann= 7 ,-1 , 0
 3847.76     .05       0  3907.6     .05       0  4574.8     .08       0
  4935.2     .04       0  5041.8     .04       0  5057.4     .08       0
  6221.2     .08       0
#XS Ineff= 2 , 0
       0    4850    82.5    5340       0    82.5
Permanent Ineff=
       F       F
Bank Sta=4935.2,5041.8
Exp/Cntr=0.5,0.3

Type RM Length L Ch R = 1 ,8884.5  ,748.7,742.2,741.9
BEGIN DESCRIPTION:
Cross Section BR 6-DS
END DESCRIPTION:
XS GIS Cut Line= 5
      3080160.51      13870298.3      3079924.97      13870133.8
      3079491.28      13870006.7       3078904.3      13869958.1
      3077891.33      13869658.6
#Sta/Elev= 30
  3815.2    83.1  3915.2    79.2  3985.2    79.4  4035.2    85.3  4055.2    88.4
  4085.2    94.7  4095.2    95.5  4152.5    92.4  4252.5    83.9  4322.5      80
  4362.5    78.8  4482.5    80.5  4604.4    80.4  4674.4    83.3  4942.9   81.75
  4974.4    79.2  4984.4    77.6  4986.8   73.93  5003.3   72.49  5010.9   73.55
  5014.4    77.6  5024.4    78.8  5060.4   79.64  5153.4    79.9  5323.4    82.2
  5763.4    82.1  5983.4    80.7  6003.4    81.7  6163.4      81    6204      82
#Mann= 4 ,-1 , 0
  3815.2     .05       0  4942.9     .04       0  5060.4     .08       0
    6204      .2       0
#XS Ineff= 2 , 0
       0 4661.29   84.92  5323.4       0   84.92
Permanent Ineff=
       F       F
Bank Sta=4974.4,5024.4
Exp/Cntr=0.3,0.1

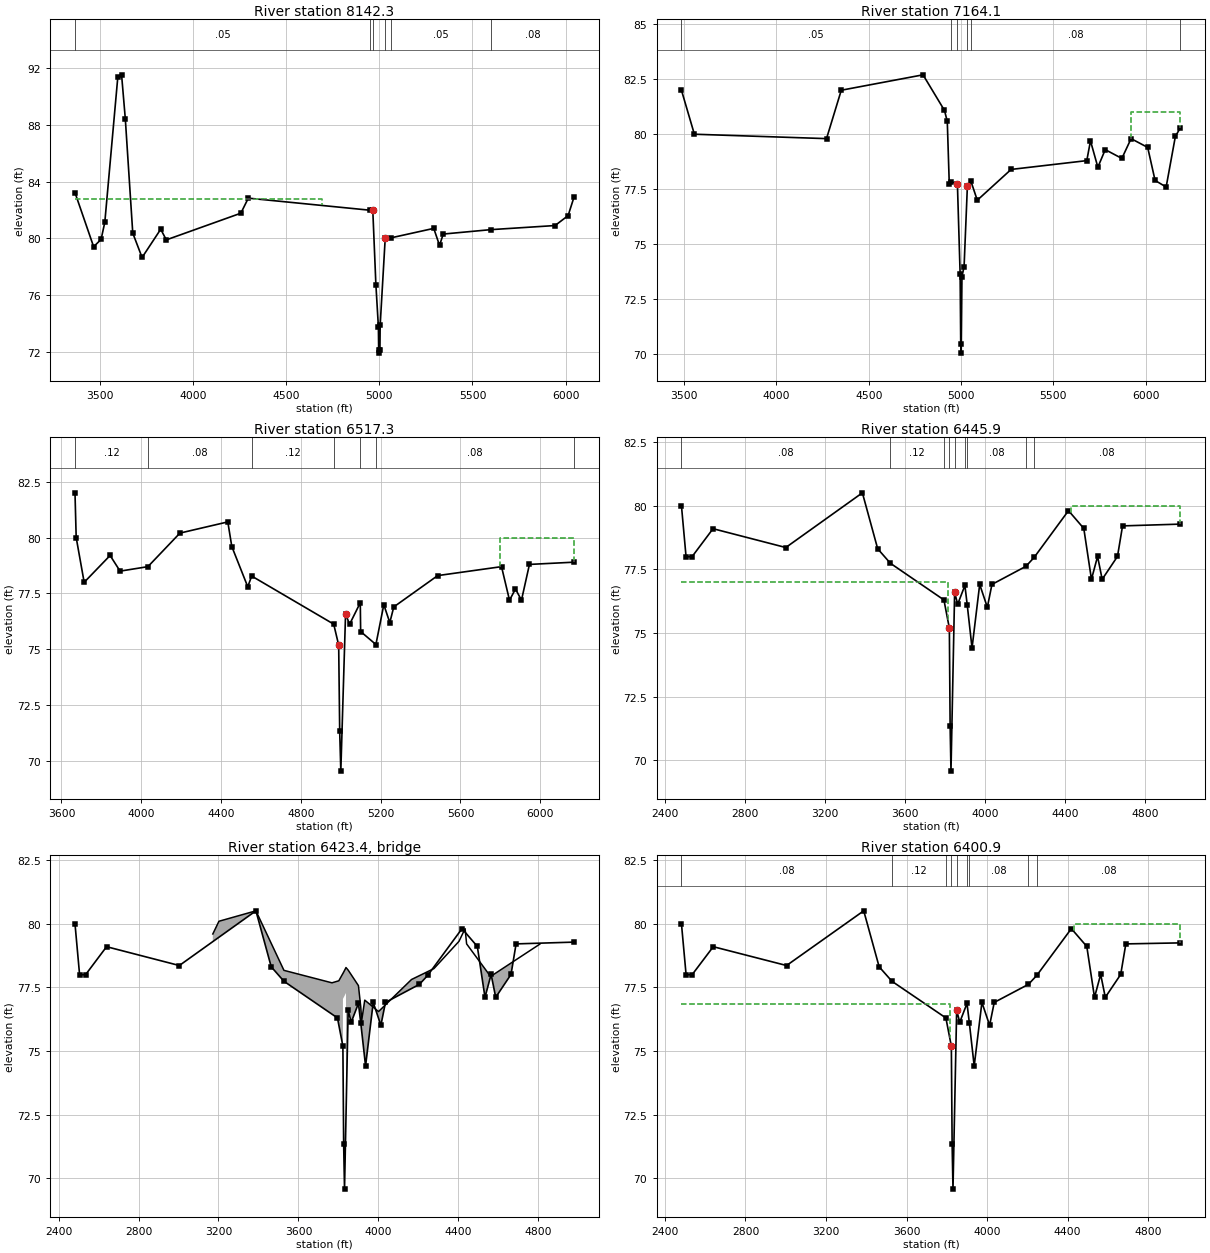
Type RM Length L Ch R = 1 ,8142.3  ,841,978.2,1107.4
BEGIN DESCRIPTION:
Cross Section X06
Located At: DS PINEMONT
END DESCRIPTION:
XS GIS Cut Line= 5
      3080175.74      13870290.1      3079380.12     13869232.34
      3079068.48     13869228.41      3078747.72     13869220.21
      3078026.51     13869195.88
#Sta/Elev= 30
  3367.2   83.22  3467.2   79.41  3507.2   79.92  3527.2   81.13  3597.2    91.4
  3617.2   91.52  3637.2   88.42  3677.2   80.37  3727.2   78.65  3827.2   80.64
  3857.2   79.89  4257.2   81.77  4297.2   82.83    4950   81.98  4965.2   81.98
  4981.8   76.74  4995.3   73.76  4996.8   72.12  5000.4   71.91  5003.5   72.15
  5004.7   73.86    5032   80.03  5065.3   80.04  5292.4    80.7  5323.3    79.5
  5343.3    80.3  5597.7   80.61  5943.3    80.9  6013.3    81.6  6044.9    82.9
#Mann= 6 ,-1 , 0
  3367.2     .05       0    4950     .04       0  4965.2     .04       0
    5032     .04       0  5065.3     .05       0  5597.7     .08       0
#XS Ineff= 2 , 0
       0  4690.8    82.8               0
Permanent Ineff=
       F       F
Bank Sta=4965.2,5032
Exp/Cntr=0.3,0.1

Type RM Length L Ch R = 1 ,7164.1  ,559.5,646.8,676.8
BEGIN DESCRIPTION:
Cross Section X05
Located At: US SOUTHERLAND RD
END DESCRIPTION:
XS GIS Cut Line= 5
      3080330.95      13870151.2      3079699.47     13869004.58
       3079711.2       13868801.      3079717.59     13868667.76
      3079045.68     13867851.06
#Sta/Elev= 30
  3485.1      82  3555.1      80  4271.1    79.8  4351.1      82  4794.1    82.7
  4910.4   81.08  4925.5   80.58  4936.3   77.73  4943.9   77.84  4980.3   77.76
  4995.1   73.65  4998.3   70.45  5000.9   70.05    5005   73.53  5016.5   73.98
  5034.4   77.64  5053.7   77.86    5088      77  5271.4    78.4  5681.4    78.8
  5701.4    79.7  5741.4    78.5  5781.4    79.3  5871.4    78.9  5921.4    79.8
  6011.4    79.4  6051.4    77.9  6111.4    77.6  6161.4    79.9    6189    80.3
#Mann= 6 ,-1 , 0
  3485.1     .05       0  4943.9     .04       0  4980.3     .04       0
  5034.4     .04       0  5053.7     .08       0    6189     .08       0
#XS Ineff= 2 , 0
       0                    5922       0      81
Permanent Ineff=
       F       F
Bank Sta=4980.3,5034.4
Exp/Cntr=0.3,0.1

Type RM Length L Ch R = 1 ,6517.3  ,72.1,71.4,59.4
BEGIN DESCRIPTION:
Cross Section BR 5-US
END DESCRIPTION:
XS GIS Cut Line= 4
      3080884.38      13869501.8      3080190.42      13868821.5
      3080205.37      13868305.6      3079720.24      13867416.1
#Sta/Elev= 30
    3668      82    3674      80    3714      78    3844    79.2    3894    78.5
  4033.5    78.7    4194    80.2    4434    80.7    4454    79.6    4534    77.8
  4553.6   78.28  4964.8   76.13  4989.7   75.19  4994.8   71.34  5000.4   69.56
  5024.2   76.59  5044.2   76.12    5098   77.09  5099.8    75.8  5176.3   75.22
  5215.9      77  5245.9    76.2  5265.9    76.9  5485.9    78.3  5805.9    78.7
  5845.9    77.2  5875.9    77.7  5905.9    77.2  5945.9    78.8  6169.2    78.9
#Mann= 7 ,-1 , 0
    3668     .12       0  4033.5     .08       0  4553.6     .12       0
  4964.8     .04       0    5098     .12       0  5176.3     .08       0
  6169.2      .2       0
#XS Ineff= 2 , 0
       0                    5800       0      80
Permanent Ineff=
       F       F
Bank Sta=4989.7,5024.2
Exp/Cntr=0.5,0.3

Type RM Length L Ch R = 1 ,6445.9  ,88.5,45,44.7
BEGIN DESCRIPTION:
Upstream Section of Bridge/Culvert/Weir
END DESCRIPTION:
XS GIS Cut Line= 6
      3080903.84      13869467.3      3080229.44     13868790.68
      3080246.97      13868399.6      3080250.16     13868345.24
      3080246.72     13868262.41  3079763.965691  13867372.36259
#Sta/Elev= 30
    2482      80    2505      78    2535      78    2640    79.13004.043   78.36
3387.219   80.513463.823   78.31 3527.48   77.743795.214    76.33822.408   75.19
3826.239   71.353830.529   69.57 3848.76    76.63864.082   76.133900.162   76.87
3911.729   76.11 3935.86   74.413974.162   76.914012.464   76.014035.445   76.91
4205.278   77.624246.567   77.974418.468   79.814495.071   79.114533.375   77.11
4564.016   78.014586.998   77.114663.602   78.014688.958   79.21 4978.73   79.28
#Mann= 9 ,-1 , 0
    2482     .08       0 3527.48     .12       03795.214     .04       0
3822.408     .04       0 3848.76     .04       03900.162     .12       0
3911.729     .08       04205.278     .05       04246.567     .08       0
#XS Ineff= 2 , 0
       03814.901      774429.146       0      80
Permanent Ineff=
       F       F
Bank Sta=3822.408,3848.76
Skew Angle= 40
Exp/Cntr=0.5,0.3

Type RM Length L Ch R = 3 ,6423.4  ,,,
Bridge Culvert--1,0,-1,-1, 0
Deck Dist Width WeirC Skew NumUp NumDn MinLoCord MaxHiCord MaxSubmerge Is_Ogee
10,25,2.6,40, 25, 25, , , 0.95, 0, 0,0,,
 3171.58 3202.22 3387.22 3527.48 3767.64 3801.96 3822.57 3822.64 3828.15 3832.15
 3837.88 3837.96 3848.76 3900.16 3911.73 3916.48  3931.8 4000.74 4165.67 4277.98
 4403.15 4433.79 4441.45 4561.41 4807.62
    79.6    80.1   80.51   78.17   77.68   77.76   78.05   78.05   78.13   78.19
   78.28   78.28   78.18   77.57   76.74    76.2      77   76.55   77.81   78.24
   79.31   79.81   79.21   77.93    79.2
                                                           77.05   77.13   77.19
   77.28
                                        
 3171.58 3202.22 3387.22 3527.48 3767.64 3801.96 3822.57 3822.64 3828.15 3832.15
 3837.88 3837.96 3848.76 3900.16 3911.73 3916.48  3931.8 4000.74 4165.67 4277.98
 4403.15 4433.79 4441.45 4561.41 4807.62
    79.6    80.1   80.51   78.17   77.68   77.76   78.05   78.05   78.13   78.19
   78.28   78.28   78.18   77.57   76.74    76.2      77   76.55   77.81   78.24
   79.31   79.81   79.21   77.93    79.2
                                                           77.05   77.13   77.19
   77.28
                                        
BR Coef=-1 , 1 , 0 ,1.25, 0 ,,,0.8,0,2,0,
WSPro=,,,, 1 ,,,, 0 ,,,, 0 ,,,,-1 ,-1 ,-1 , 0 , 0 , 0 , 0 , 0
BC Design=,, 0 ,, 0 ,,,,,,
BC HTab HWMax=80.51

Type RM Length L Ch R = 1 ,6400.9  ,120,85.5,60.8
BEGIN DESCRIPTION:
Downstream Section of Bridge/Culvert/Weir
END DESCRIPTION:
XS GIS Cut Line= 6
      3080936.96      13869445.8      3080271.87     13868778.51
       3080288.8     13868400.82      3080292.07     13868345.16
      3080287.99     13868247.03  3079812.546926  13867362.64635
#Sta/Elev= 30
    2482      80    2505      78    2535      78    2640    79.13004.043   78.36
3387.219   80.513463.823   78.31 3527.48   77.743795.214    76.33822.408   75.19
3826.239   71.353830.529   69.57 3848.76    76.63864.082   76.133900.162   76.87
3911.729   76.11 3935.86   74.413974.162   76.914012.464   76.014035.445   76.91
4205.278   77.624246.567   77.974418.468   79.814495.071   79.114533.375   77.11
4564.016   78.014586.998   77.114663.602   78.014688.958   79.214960.299   79.25
#Mann= 9 ,-1 , 0
    2482     .08       0 3527.48     .12       03795.214     .04       0
3822.408     .04       0 3848.76     .04       03900.162     .12       0
3911.729     .08       04205.278     .05       04246.567     .08       0
#XS Ineff= 2 , 0
       03814.901   76.854429.146       0      80
Permanent Ineff=
       F       F
Bank Sta=3822.408,3848.76
Skew Angle= 40
Exp/Cntr=0.5,0.3

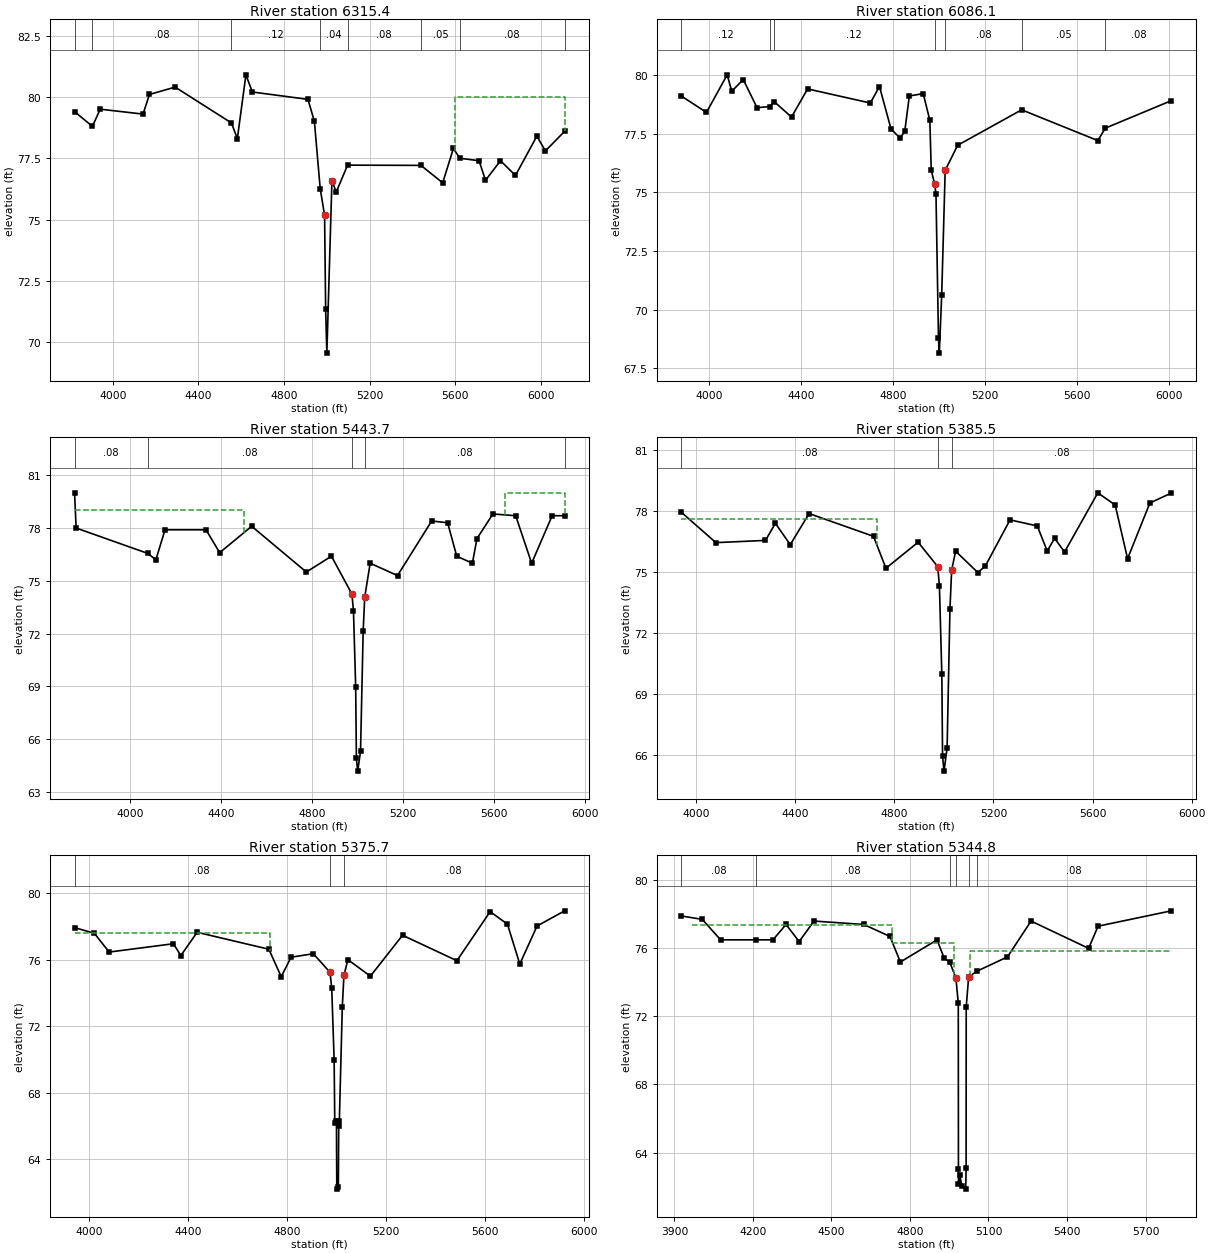
Type RM Length L Ch R = 1 ,6315.4  ,245.8,229.3,196.4
BEGIN DESCRIPTION:
Cross Section BR 5-DS
END DESCRIPTION:
XS GIS Cut Line= 5
      3080855.91      13869296.3      3080321.27      13868769.2
      3080351.18      13868391.6      3080347.44      13868230.8
      3079873.04      13867350.7
#Sta/Elev= 30
  3821.4    79.4  3904.9    78.8  3941.4    79.5  4141.4    79.3  4171.4    80.1
  4291.4    80.4  4554.6   78.94  4582.2    78.3  4622.2    80.9  4652.2    80.2
  4912.2    79.9  4942.2      79  4969.4   76.26  4989.8   75.18  4994.8   71.34
  5000.4   69.56  5024.2   76.59  5044.2   76.12  5097.2   77.22    5440   77.21
  5541.8    76.5  5591.8    77.9  5622.1    77.5  5711.8    77.4  5741.8    76.6
  5811.8    77.4  5881.8    76.8  5981.8    78.4  6021.8    77.8  6111.8    78.6
#Mann= 8 ,-1 , 0
  3821.4     .12       0  3904.9     .08       0  4554.6     .12       0
  4969.4     .04       0  5097.2     .08       0    5440     .05       0
  5622.1     .08       0  6111.8     .08       0
#XS Ineff= 2 , 0
       0                    5600       0      80
Permanent Ineff=
       F       F
Bank Sta=4989.8,5024.2
Exp/Cntr=0.3,0.1

Type RM Length L Ch R = 1 ,6086.1  ,598.2,642.4,643.4
BEGIN DESCRIPTION:
Cross-section 6086.1
Interpolated Section
END DESCRIPTION:
XS GIS Cut Line= 3
      3081109.81     13869128.92     3080749.532     13868696.59
  3080100.94335613867266.7481559
#Sta/Elev= 30
  3877.4    79.1  3987.4    78.4  4077.4      80  4097.4    79.3  4147.4    79.8
  4207.4    78.6  4262.6   78.65  4281.9   78.86  4357.4    78.2  4427.4    79.4
  4700.2    78.8  4740.2    79.5  4790.2    77.7  4830.2    77.3  4850.2    77.6
  4870.2    79.1 4930.54    79.2 4959.37   78.06 4965.37   75.94 4979.83   75.37
    4986   74.94 4996.94   68.78 5000.47   68.15 5010.88   70.61 5026.11   75.93
  5080.2      77  5358.9   78.51  5690.2    77.2  5722.9   77.73  6010.2    78.9
#Mann= 7 ,-1 , 0
  3877.4     .12       0  4262.6     .08       0  4281.9     .12       0
 4979.83     .04       0 5026.11     .08       0  5358.9     .05       0
  5722.9     .08       0
Bank Sta=4979.83,5026.11
Exp/Cntr=0.3,0.1

Type RM Length L Ch R = 1 ,5443.7  ,57.3,58.2,60.5
BEGIN DESCRIPTION:
Cross Section XS 5443.7
END DESCRIPTION:
XS GIS Cut Line= 4
      3081628.19       13868743.      3081181.87      13868260.4
      3080776.08      13867293.3      3080556.12      13866906.5
#Sta/Elev= 30
    3758      80    3765      78  4078.9   76.56    4115    76.2    4155    77.9
    4335    77.9    4395    76.6  4535.4    78.1  4775.4    75.5  4885.4    76.4
 4975.35   74.25 4982.16    73.3 4991.91   68.96 4994.91   64.91 5000.66   64.19
 5013.17   65.32 5024.74   72.16 5031.46   74.07  5055.4      76  5175.4    75.3
  5325.4    78.4  5395.4    78.3  5435.4    76.4  5504.1      76  5524.1    77.4
  5594.1    78.8  5694.1    78.7  5764.1      76  5854.1    78.7  5909.1    78.7
#Mann= 5 ,-1 , 0
    3758     .08       0  4078.9     .08       0 4975.35     .04       0
 5031.46     .08       0  5909.1      .2       0
#XS Ineff= 2 , 0
       0    4500      79 5647.18       0      80
Permanent Ineff=
       F       F
Bank Sta=4975.35,5031.46
Exp/Cntr=0.3,0.1

Type RM Length L Ch R = 1 ,5385.5  ,9.6,9.8,10.3
BEGIN DESCRIPTION:
Drop structure u/s Bingle Rd.  (u/s section)
END DESCRIPTION:
XS GIS Cut Line= 5
      3081548.75      13868576.5      3081221.25     13868204.08
       3081002.2     13867687.75      3080808.03     13867222.41
  3080597.634491   13866862.7822
#Sta/Elev= 30
  3940.3   77.93  4080.3   76.43  4280.3   76.54  4320.3   77.38  4380.3   76.33
  4456.3   77.86  4716.3   76.74  4766.3   75.17  4896.3   76.45  4975.4   75.25
  4982.2    74.3  4991.9   69.96  4994.9   65.91  5000.7   65.19  5013.2   66.32
  5024.7   73.16  5031.5   75.07  5047.6   76.01  5137.1   74.96  5167.1   75.27
  5267.1   77.55  5377.1   77.25  5417.1   76.02  5447.1   76.64  5487.1   75.97
  5621.4   78.88  5691.4   78.28  5741.4   75.64  5831.4   78.38    5918   78.87
#Mann= 3 ,-1 , 0
  3940.3     .08       0  4975.4     .04       0  5031.5     .08       0
#XS Ineff= 2 , 0
       0    4730   77.59 5630.08       0   78.78
Permanent Ineff=
       F       F
Bank Sta=4975.4,5031.5
Exp/Cntr=0.3,0.1

Type RM Length L Ch R = 1 ,5375.7  ,29.9,30.9,32.1
BEGIN DESCRIPTION:
Drop structure u/s Bingle Rd.  (d/s section)
END DESCRIPTION:
XS GIS Cut Line= 5
      3081556.91      13868571.1       3081229.4     13868198.68
      3081010.36     13867682.36      3080816.19     13867217.02
      3080607.27  13866850.73488
#Sta/Elev= 30
  3940.3   77.94  4020.3    77.6  4080.3   76.47  4340.3   76.97  4370.3   76.26
  4436.3   77.66  4726.3   76.64  4776.3   74.99  4816.3   76.16  4906.3   76.37
  4973.8   75.25  4980.7    74.3  4990.4   69.96    4993   66.21  4999.7    66.3
  5001.2   62.21  5007.4   62.31    5009      66  5011.5   66.32  5023.4   73.16
    5030   75.07  5046.1   76.01  5137.1   75.02  5267.1   77.48  5487.1   75.95
  5621.4    78.9  5691.4   78.15  5741.4   75.75  5811.4   78.04    5923   78.95
#Mann= 3 ,-1 , 0
  3940.3     .08       0  4973.8     .04       0    5030     .08       0
#XS Ineff= 2 , 0
       0    4730   77.59 5630.08       0   78.78
Permanent Ineff=
       F       F
Bank Sta=4973.8,5030
Exp/Cntr=0.5,0.3

Type RM Length L Ch R = 1 ,5344.8  ,113.6,128,117.8
BEGIN DESCRIPTION:
Upstream Section of Bridge/Culvert/Weir
END DESCRIPTION:
XS GIS Cut Line= 5
      3081583.06     13868560.72      3081256.73     13868186.03
      3081033.81      13867662.3      3080836.05     13867185.67
      3080691.27      13866933.8
#Sta/Elev= 30
  3926.1   77.87  4006.6   77.67  4076.6   76.47  4210.5   76.47  4276.6   76.47
  4326.6   77.37  4376.6   76.37  4433.5   77.57  4623.5   77.37  4723.5   76.67
  4763.5   75.17  4903.5   76.47  4931.3   75.38  4951.8   75.18  4975.6   74.23
  4984.7   72.76  4985.3   63.05  4985.5   62.18  4990.3   62.69  4998.4   62.04
  5013.1   61.86  5014.6   63.07    5015   72.53  5024.3    74.3    5057   74.64
  5172.7   75.47  5262.7   77.57  5482.7   75.97  5518.7   77.27  5798.7   78.17
#Mann= 6 ,-1 , 0
  3926.1     .08       0  4210.5     .08       0  4951.8     .04       0
  4975.6     .03       0  5024.3     .04       0    5057     .08       0
#XS Ineff= 3 ,-1
 3965.84    4730   77.32    4730 4969.39   76.26 5030.97  6101.2   75.79
Permanent Ineff=
       F       F       F
Bank Sta=4975.6,5024.3
Exp/Cntr=0.5,0.3