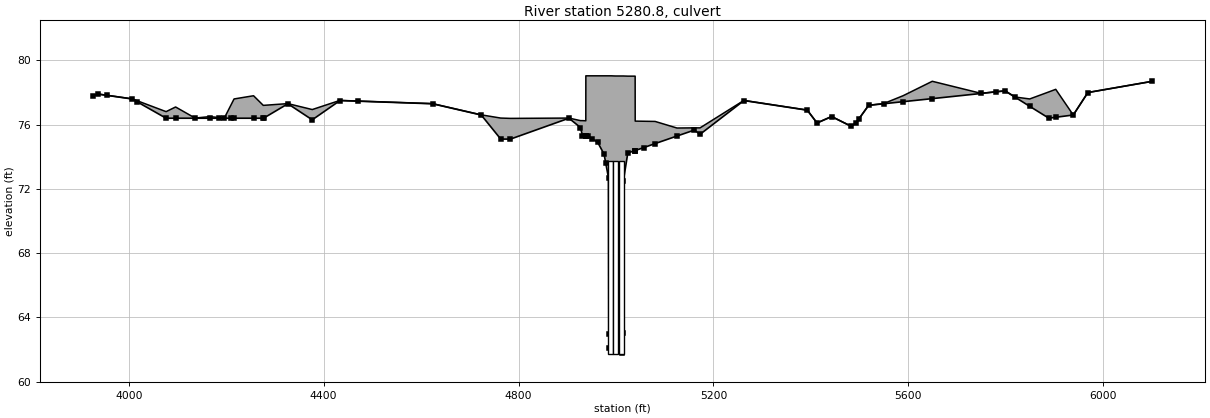
HEC-RAS study E115-04-00.prj: E115-04-00

--- E115-04-00.g01 (geometry) --- (continued)

Type RM Length L Ch R = 2 ,5280.8  ,,,
BEGIN DESCRIPTION:
BINGLE ROAD
Structure ID: E115-04-00-04
END DESCRIPTION:
Bridge Culvert--1,0,-1,-1, 0
Deck Dist Width WeirC Skew NumUp NumDn MinLoCord MaxHiCord MaxSubmerge Is_Ogee
10,108,2.6,0, 60, 60, , , 0.95, 0, ,,,
  3926.1  3936.6  4006.6  4076.6  4096.1  4136.1  4166.1  4196.1  4216.1  4256.1
  4276.1  4326.6  4376.6  4433.5  4623.5  4723.5  4763.5  4783.5  4903.5  4927.2
  4931.3 4938.09  4938.2  4942.7  4962.5  4975.6  4984.7  4985.3  4985.5  4990.3
  4998.4  5013.1  5014.6    5015  5024.3  5039.4 5039.51  5080.4  5125.2  5160.8
  5172.7  5262.7  5392.7  5412.7  5442.7  5482.7  5492.7  5518.7  5549.3  5589.3
  5649.3  5749.3  5798.7  5819.3  5849.3  5888.7  5902.7  5938.7  5968.7  6101.2
    77.8   77.91   77.61   76.81    77.1   76.41    76.5   76.41    77.6    77.8
    77.2   77.31   76.94   77.51   77.31   76.61   76.41   76.39   76.41   76.25
   76.25   76.24   79.04   79.04   79.04   79.04   79.04   79.04   79.04   79.04
   79.03   79.03   79.03   79.03   79.02   79.02   76.22    76.2   75.79    75.8
    75.8   77.51   76.91   76.11   76.51    75.9   76.11   77.21   77.31    77.8
    78.7   77.95   78.11   77.72    77.6   78.04    78.2    76.6      78    78.7
    77.8    77.9    77.6    76.4    76.4    76.4    76.4    76.4    76.4    76.4
    76.4    77.3    76.3    77.5    77.3    76.6    75.1    75.1    76.4   75.82
   75.31   75.29   75.29   75.28    74.9   74.16   72.69   62.98   62.11   62.62
   61.97   61.79      63   72.46   74.23   74.39   74.39   74.82   75.29   75.66
    75.4    77.5    76.9    76.1    76.5    75.9    76.1    77.2    77.3   77.43
   77.62   77.94    78.1   77.71   77.14    76.4   76.46    76.6      78    78.7
  3926.1  3936.6  4006.6  4076.6  4096.1  4136.1  4166.1  4196.1  4216.1  4256.1
  4276.1  4326.6  4376.6  4433.5  4623.5  4723.5  4763.5  4783.5  4903.5  4927.2
  4931.3 4938.09  4938.2  4942.7  4962.5  4975.6  4984.7  4985.3  4985.5  4990.3
  4998.4  5013.1  5014.6    5015  5024.3  5039.4 5039.51  5080.4  5125.2  5160.8
  5172.7  5262.7  5392.7  5412.7  5442.7  5482.7  5492.7  5518.7  5549.3  5589.3
  5649.3  5749.3  5798.7  5819.3  5849.3  5888.7  5902.7  5938.7  5968.7  6101.2
    77.8   77.91   77.61   76.81    77.1   76.41    76.5   76.41    77.6    77.8
    77.2   77.31   76.94   77.51   77.31   76.61   76.41   76.39   76.41   76.25
   76.25   76.24   79.04   79.04   79.04   79.04   79.04   79.04   79.04   79.04
   79.03   79.03   79.03   79.03   79.02   79.02   76.22    76.2   75.79    75.8
    75.8   77.51   76.91   76.11   76.51    75.9   76.11   77.21   77.31    77.8
    78.7   77.95   78.11   77.72    77.6   78.04    78.2    76.6      78    78.7
   77.66   77.76   77.46   76.26   76.26   76.26   76.26   76.26   76.26   76.26
   76.26   77.16   76.16   77.36   77.16   76.46   74.96   74.96   76.26   75.68
   75.17   75.15   75.15   75.14   74.76   74.02   72.55   62.84   61.97   62.48
   61.83   61.65   62.86   72.32   74.09   74.25   74.25   74.68   75.15   75.52
   75.26   77.36   76.76   75.96   76.36   75.76   75.96   77.06   77.16   77.29
   77.48    77.8   77.96   77.57      77   76.26   76.32   76.46   77.86   78.56
BR Coef= 1 , 1 , 1 ,1.25, 0 ,,,0.8,0,2,0,
WSPro=,,,, 1 ,,,, 0 ,,,, 0 ,,,,-1 ,-1 ,-1 , 0 , 0 , 0 , 0 , 0
Culvert=2,12,10,108,0.015,0.5,1,8,1,61.71,4989.1,61.67,4989.1,Culvert #1  , 0 ,10
Culvert Bottom n=0.015
Culvert=2,12,10,108,0.02,0.4,1,8,1,61.72,4999.8,61.66,4999.8,Culvert #2  , 0 ,10
Culvert Bottom n=0.02
Culvert=2,12,10,108,0.02,0.4,1,8,1,61.73,5010.5,61.66,5010.5,Culvert #3  , 0 ,10
Culvert Bottom n=0.02
BR U #Sta/Elev= 74
  3926.1    77.8  3936.6    77.9  3956.1   77.82  4006.6    77.6  4016.1   77.44
  4076.6    76.4  4096.1    76.4  4136.1    76.4  4166.1    76.4  4186.1    76.4
  4196.1    76.4  4210.5    76.4  4216.1    76.4  4256.1    76.4  4276.1    76.4
  4276.6    76.4  4326.6    77.3  4376.6    76.3  4433.5    77.5    4471   77.46
  4623.5    77.3  4723.5    76.6  4763.5    75.1  4783.5    75.1  4903.5    76.4
  4927.2   75.82  4931.3   75.31 4938.09   75.29  4938.2   75.29 4938.31   75.29
  4942.7   75.28  4951.8   75.11  4962.5    74.9  4975.6   74.16  4978.8   73.64
  4984.7   72.69  4985.3   62.98  4985.5   62.11  4990.3   62.62  4998.4   61.97
  5005.7   61.93  5013.1   61.79  5014.6      63    5015   72.46  5024.3   74.23
 5039.29   74.39  5039.4   74.39 5039.51   74.39    5057   74.57  5080.4   74.82
  5125.2   75.29  5160.8   75.66  5172.7    75.4  5262.7    77.5  5392.7    76.9
  5412.7    76.1  5442.7    76.5  5482.7    75.9  5492.7    76.1  5499.3   76.38
  5518.7    77.2  5549.3    77.3  5589.3   77.43  5649.3   77.62  5749.3   77.94
  5779.3   78.04  5798.7    78.1  5819.3   77.71  5849.3   77.14  5888.7    76.4
  5902.7   76.46  5938.7    76.6  5968.7      78  6101.2    78.7
BR U #Mann= 6
  3926.1     .08  4210.5     .08  4951.8     .04  4975.6    .015  5024.3     .04
    5057     .08
BR U Banks=4975.6,5024.3
BR D #Sta/Elev= 74
  3926.1    77.8  3936.6    77.9  3956.1   77.82  4006.6    77.6  4016.1   77.44
  4076.6    76.4  4096.1    76.4  4136.1    76.4  4166.1    76.4  4186.1    76.4
  4196.1    76.4  4210.5    76.4  4216.1    76.4  4256.1    76.4  4276.1    76.4
  4276.6    76.4  4326.6    77.3  4376.6    76.3  4433.5    77.5    4471   77.46
  4623.5    77.3  4723.5    76.6  4763.5    75.1  4783.5    75.1  4903.5    76.4
  4927.2   75.82  4931.3   75.31 4938.09   75.29  4938.2   75.29 4938.31   75.29
  4942.7   75.28  4951.8   75.11  4962.5    74.9  4975.6   74.16  4978.8   73.64
  4984.7   72.69  4985.3   62.98  4985.5   62.11  4990.3   62.62  4998.4   61.97
  5005.7   61.93  5013.1   61.79  5014.6      63    5015   72.46  5024.3   74.23
 5039.29   74.39  5039.4   74.39 5039.51   74.39    5057   74.57  5080.4   74.82
  5125.2   75.29  5160.8   75.66  5172.7    75.4  5262.7    77.5  5392.7    76.9
  5412.7    76.1  5442.7    76.5  5482.7    75.9  5492.7    76.1  5499.3   76.38
  5518.7    77.2  5549.3    77.3  5589.3   77.43  5649.3   77.62  5749.3   77.94
  5779.3   78.04  5798.7    78.1  5819.3   77.71  5849.3   77.14  5888.7    76.4
  5902.7   76.46  5938.7    76.6  5968.7      78  6101.2    78.7
BR D #Mann= 6
  3926.1     .08  4210.5     .08  4951.8     .04  4975.6    .015  5024.3     .04
    5057     .08
BR D Banks=4975.6,5024.3
BC Design=,, 0 ,, 0 ,,,,,,
BC HTab HWMax=78.77