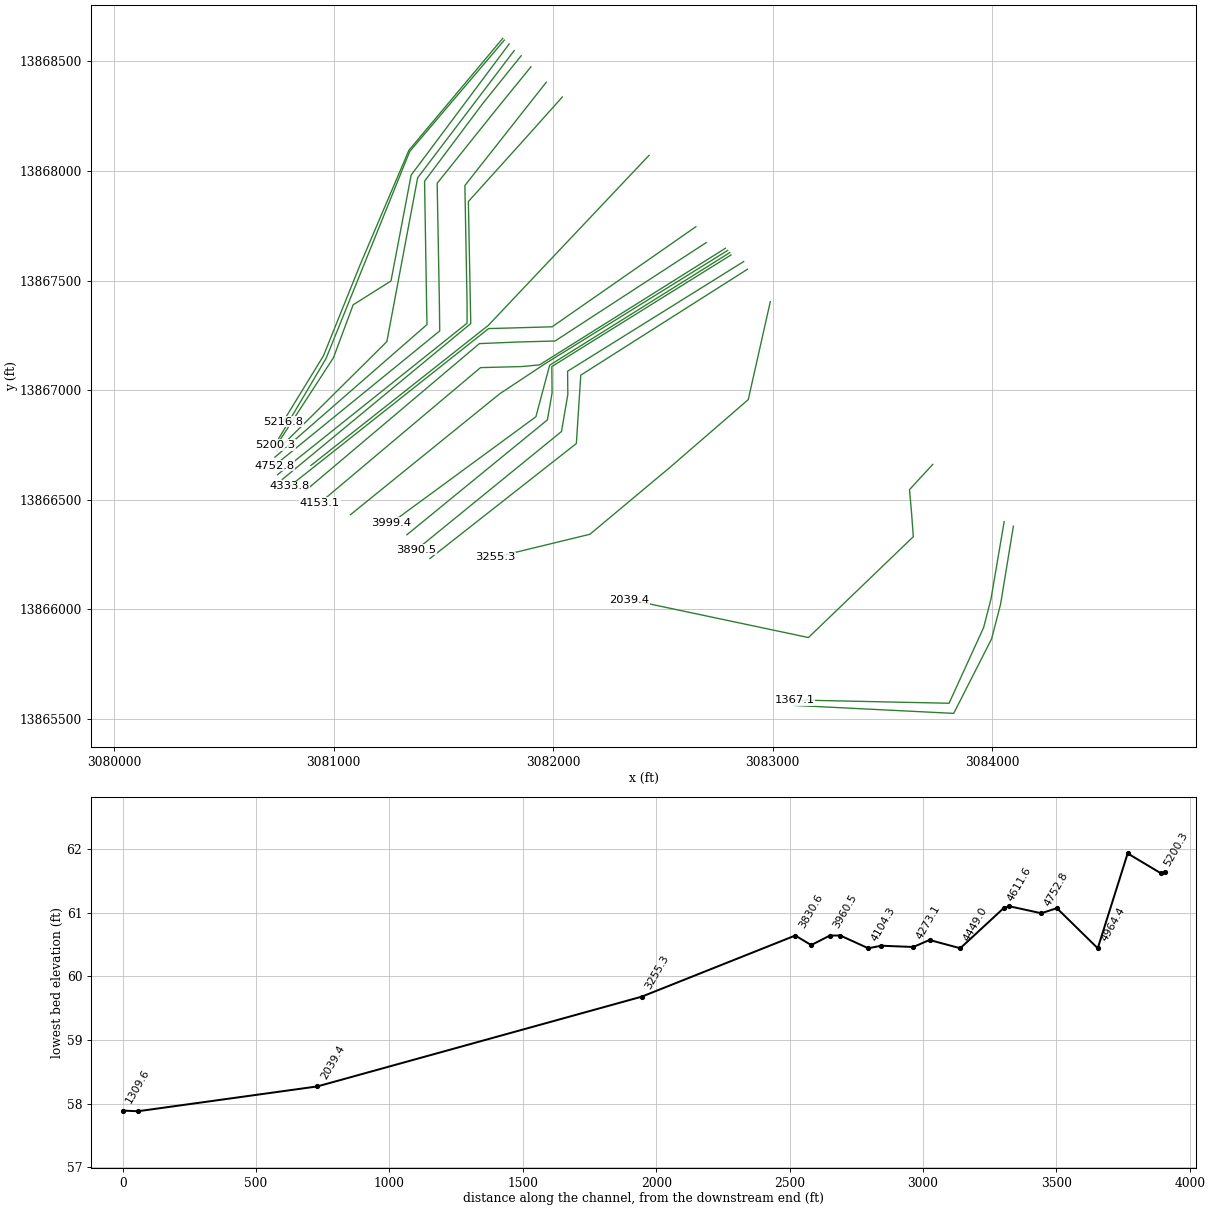
HEC-RAS study E115-04-00.prj: E115-04-00

--- E115-04-00.g01 (geometry) --- (continued)

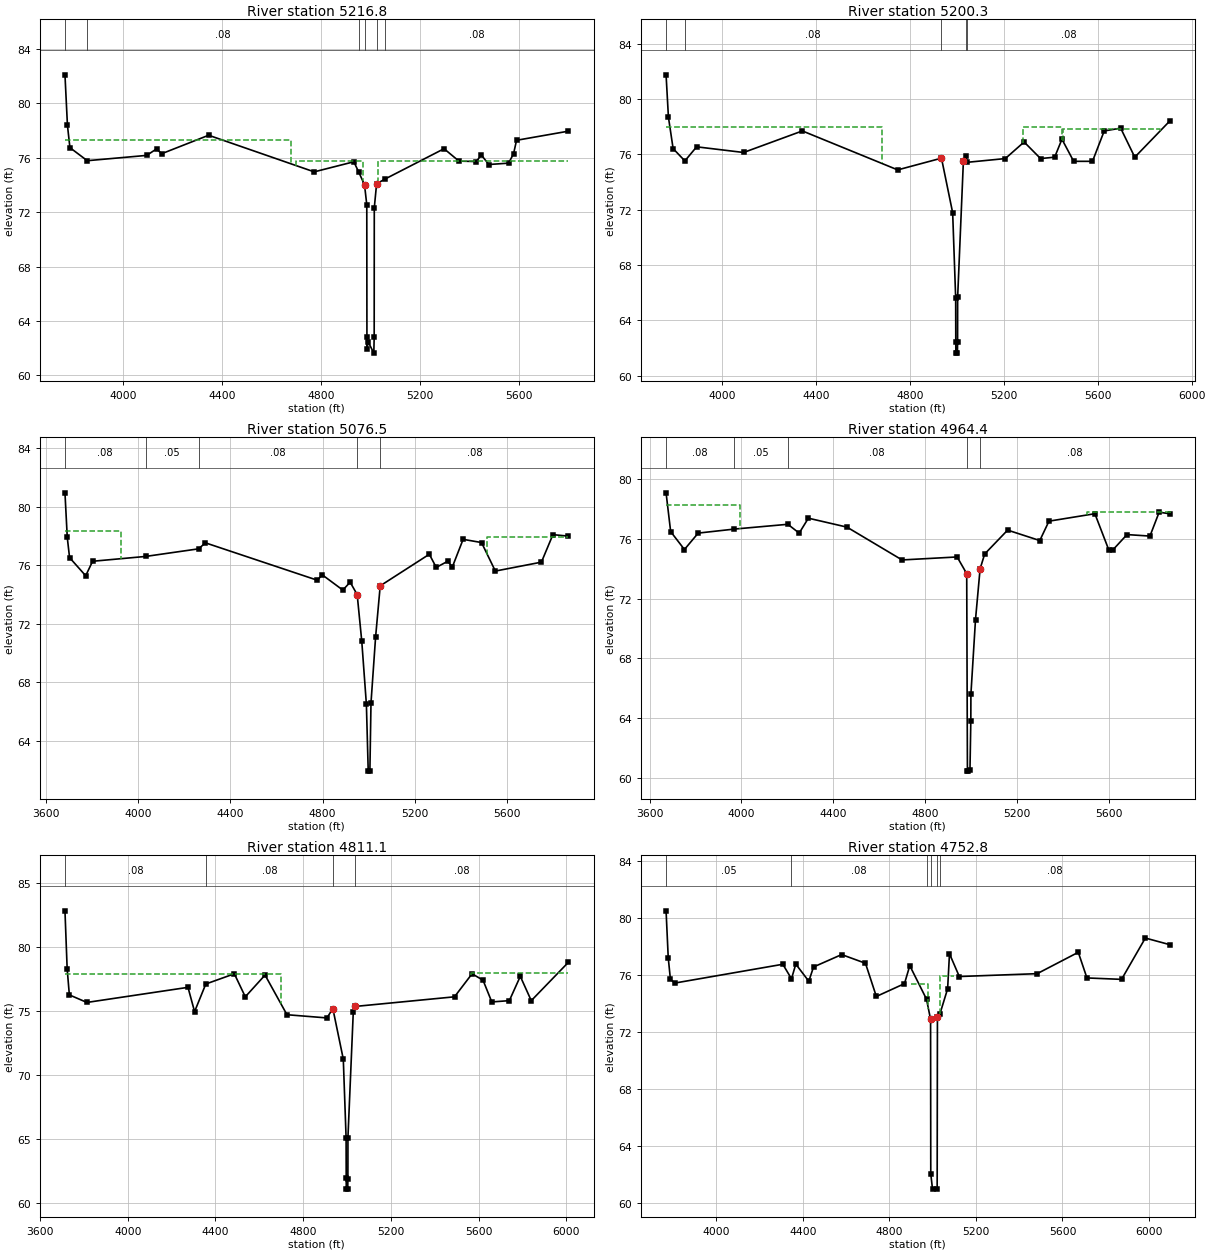
Type RM Length L Ch R = 1 ,5216.8  ,8.4,16.5,16.6
BEGIN DESCRIPTION:
Downstream Section of Bridge/Culvert/Weir
END DESCRIPTION:
XS GIS Cut Line= 5
      3081770.74      13868604.5      3081343.01      13868093.9
      3081122.01      13867574.7      3080953.75      13867156.8
       3080770.2      13866856.9
#Sta/Elev= 30
  3766.3   82.09  3776.3   78.38  3786.3   76.74  3856.3   75.78  4096.3   76.17
  4136.3   76.65  4156.3   76.29  4346.3   77.65  4772.4   74.96  4932.4    75.7
  4951.8   74.96  4975.6   74.01  4984.7   72.54  4985.3   62.83  4985.5   61.96
  4990.3   62.47  5013.1   61.64  5014.6   62.85    5015   72.31  5024.3   74.08
    5057   74.42  5296.7   76.66  5356.7   75.75  5426.7   75.72  5447.2    76.2
  5477.2    75.5  5557.2    75.6  5577.2   76.29  5589.3   77.28  5798.7   77.95
#Mann= 6 ,-1 , 0
  3766.3     .02       0  3856.3     .08       0  4951.8     .04       0
  4975.6    .015       0  5024.3     .04       0    5057     .08       0
#XS Ineff= 3 ,-1
  3766.3    4680   77.32 4700.53 4969.39   75.79 5030.97  6101.2   75.79
Permanent Ineff=
       F       F       F
Bank Sta=4975.6,5024.3
Exp/Cntr=0.5,0.3

Type RM Length L Ch R = 1 ,5200.3  ,53,123.8,103.8
BEGIN DESCRIPTION:
Cross Section X03.65
END DESCRIPTION:
XS GIS Cut Line= 4
       3081777.8      13868596.3      3081346.84      13868088.7
      3080965.69      13867144.7  3080732.564451  13866749.53741
#Sta/Elev= 30
  3763.1   81.76  3773.1    78.7  3793.1   76.42  3843.1   75.53  3893.1   76.55
  4093.1   76.14  4343.1    77.7  4748.9   74.88  4935.2   75.73  4982.8   71.78
  4995.6   65.62  4996.1   62.46  4996.4   61.62  5003.1   61.64  5003.8   62.45
    5004   65.65  5028.4   75.49  5038.4    75.9  5045.1   75.43  5206.9    75.7
  5286.9    76.9  5356.9    75.7  5416.9    75.8  5447.9    77.1  5497.9    75.5
  5577.9    75.5  5627.9    77.7  5697.9    77.9  5757.9    75.8  5905.8    78.4
#Mann= 5 ,-1 , 0
  3763.1     .02       0  3843.1     .08       0  4935.2    .015       0
  5038.4     .04       0  5045.1     .08       0
#XS Ineff= 3 ,-1
 5282.93 5446.34      78 5451.22 5865.85   77.87  3763.1    4680      78
Permanent Ineff=
       F       F       F
Bank Sta=4935.2,5028.4
Exp/Cntr=0.3,0.1

Type RM Length L Ch R = 1 ,5076.5  ,42,112.1,91.4
BEGIN DESCRIPTION:
Cross Section XS 3.63
END DESCRIPTION:
XS GIS Cut Line= 6
      3081800.03       13868579.      3081353.29     13867980.84
      3081261.41     13867497.73      3081088.94     13867389.14
      3080999.51     13867148.53      3080734.36      13866739.7
#Sta/Elev= 30
  3681.6   80.96  3691.6   77.91  3701.6   76.53  3771.6   75.29  3801.6   76.28
  4031.6   76.61  4261.6   77.13  4291.6   77.54  4778.2   74.98  4798.2   75.36
  4888.2   74.31    4920   74.85  4950.5      74  4970.5    70.8  4990.5    66.5
  4998.4   61.97  5005.7   61.93  5010.5    66.6  5030.5    71.1  5050.5    74.6
  5263.8   76.76  5293.8   75.86  5343.8   76.28  5363.8   75.89  5410.5   77.78
  5490.5   77.56  5550.5   75.61  5750.5   76.22  5800.5    78.1  5867.8      78
#Mann= 5 ,-1 , 0
  3681.6     .08       0  4031.6     .05       0  4261.6     .08       0
  4950.5    .015       0  5050.5     .08       0
#XS Ineff= 2 , 0
         3923.39   78.34 5516.13           77.96
Permanent Ineff=
       F       F
Bank Sta=4950.5,5050.5
Exp/Cntr=0.3,0.1

Type RM Length L Ch R = 1 ,4964.4  ,53.2,153.3,82.4
BEGIN DESCRIPTION:
Cross Section XS 3.62
END DESCRIPTION:
XS GIS Cut Line= 4
      3081822.79      13868548.6      3081382.87      13867968.4
      3081242.55      13867221.3      3080741.95      13866724.5
#Sta/Elev= 30
  3672.2    79.1  3692.2    76.5  3752.2    75.3  3812.2    76.4  3970.1   76.67
  4202.7   76.99  4252.2    76.4  4292.2    77.4  4460.4    76.8  4700.4    74.6
  4940.4    74.8  4982.1   73.68  4985.2   60.48  4989.8   60.44  4996.3   60.51
    5000   63.81  5000.4    65.6  5020.4    70.6  5040.4      74  5060.4      75
  5160.4    76.6  5300.5    75.9  5340.5    77.2  5540.5    77.7  5600.5    75.3
  5620.5    75.3  5680.5    76.3  5780.5    76.2  5820.5    77.8  5865.8    77.7
#Mann= 5 ,-1 , 0
  3672.2     .08       0  3970.1     .05       0  4202.7     .08       0
  4982.1    .015       0  5040.4     .08       0
#XS Ineff= 2 , 0
         3993.95   78.29 5506.05           77.79
Permanent Ineff=
       F       F
Bank Sta=4982.1,5040.4
Exp/Cntr=0.3,0.1

Type RM Length L Ch R = 1 ,4811.1  ,57.2,58.3,76.2
BEGIN DESCRIPTION:
Cross Section X03.6
END DESCRIPTION:
XS GIS Cut Line= 6
       3081854.5       13868525.      3081678.79      13868306.3
      3081414.43     13867952.92      3081423.66     13867391.53
      3081425.47     13867299.12  3080732.564451  13866694.11975
#Sta/Elev= 30
  3713.7   82.82  3723.7   78.29  3733.7   76.25  3813.7   75.66  4274.7   76.84
  4304.7   74.94  4355.8    77.1    4486    77.9    4536    76.1    4626    77.8
    4726    74.7  4908.2   74.45  4935.2   75.18  4982.8   71.23  4995.6   65.07
  4996.1   61.91  4996.4   61.07  5003.1   61.09  5003.8    61.9    5004    65.1
  5028.4   74.94  5038.4   75.35  5489.9    76.1  5569.9    77.9  5619.9    77.4
  5659.9    75.7  5739.9    75.8  5789.9    77.7  5839.9    75.8 6009.32    78.8
#Mann= 4 ,-1 , 0
  3713.7     .08       0  4355.8     .08       0  4935.2    .015       0
  5038.4     .08       0
#XS Ineff= 2 , 0
       0    4700   77.87 5565.85       0      78
Permanent Ineff=
       F       F
Bank Sta=4935.2,5038.4
Exp/Cntr=0.5,0.3

Type RM Length L Ch R = 1 ,4752.8  ,139.4,120,64.4
BEGIN DESCRIPTION:
Upstream Section of Bridge/Culvert/Weir
END DESCRIPTION:
XS GIS Cut Line= 6
       3081899.1      13868474.5      3081741.64     13868280.76
      3081471.79     13867943.46      3081481.95     13867397.65
      3081483.48       13867270.  3080730.154987  13866655.56833
#Sta/Elev= 30
  3767.7   80.52  3777.7   77.23  3787.7   75.72  3807.7   75.45  4307.4   76.77
  4347.4   75.75  4367.4   76.78  4427.4   75.58  4449.4   76.58  4579.4   77.45
  4689.4   76.84  4739.7   74.51  4869.7   75.41  4894.3   76.67  4971.6   74.32
  4990.4    72.9  4991.3   62.06  4999.4   60.99 5020.83      61  5022.1   73.06
  5033.7   73.29  5069.2   75.05  5077.8   77.51  5123.2   75.91  5483.2   76.11
  5673.2   77.61  5713.2   75.81  5873.2   75.71  5983.2   78.61    6095   78.15
#Mann= 6 ,-1 , 0
  3767.7     .05       0  4347.4     .08       0  4971.6     .04       0
  4990.4    .015       0  5022.1     .04       0  5033.7     .08       0
#XS Ineff= 4 ,-1
  3767.7    4575   76.93 4901.08  4980.4   75.37  5032.1 5100.95   75.94
 5673.44 5954.61   77.55
Permanent Ineff=
       T       F       F       T
Bank Sta=4990.4,5022.1
Exp/Cntr=0.5,0.3

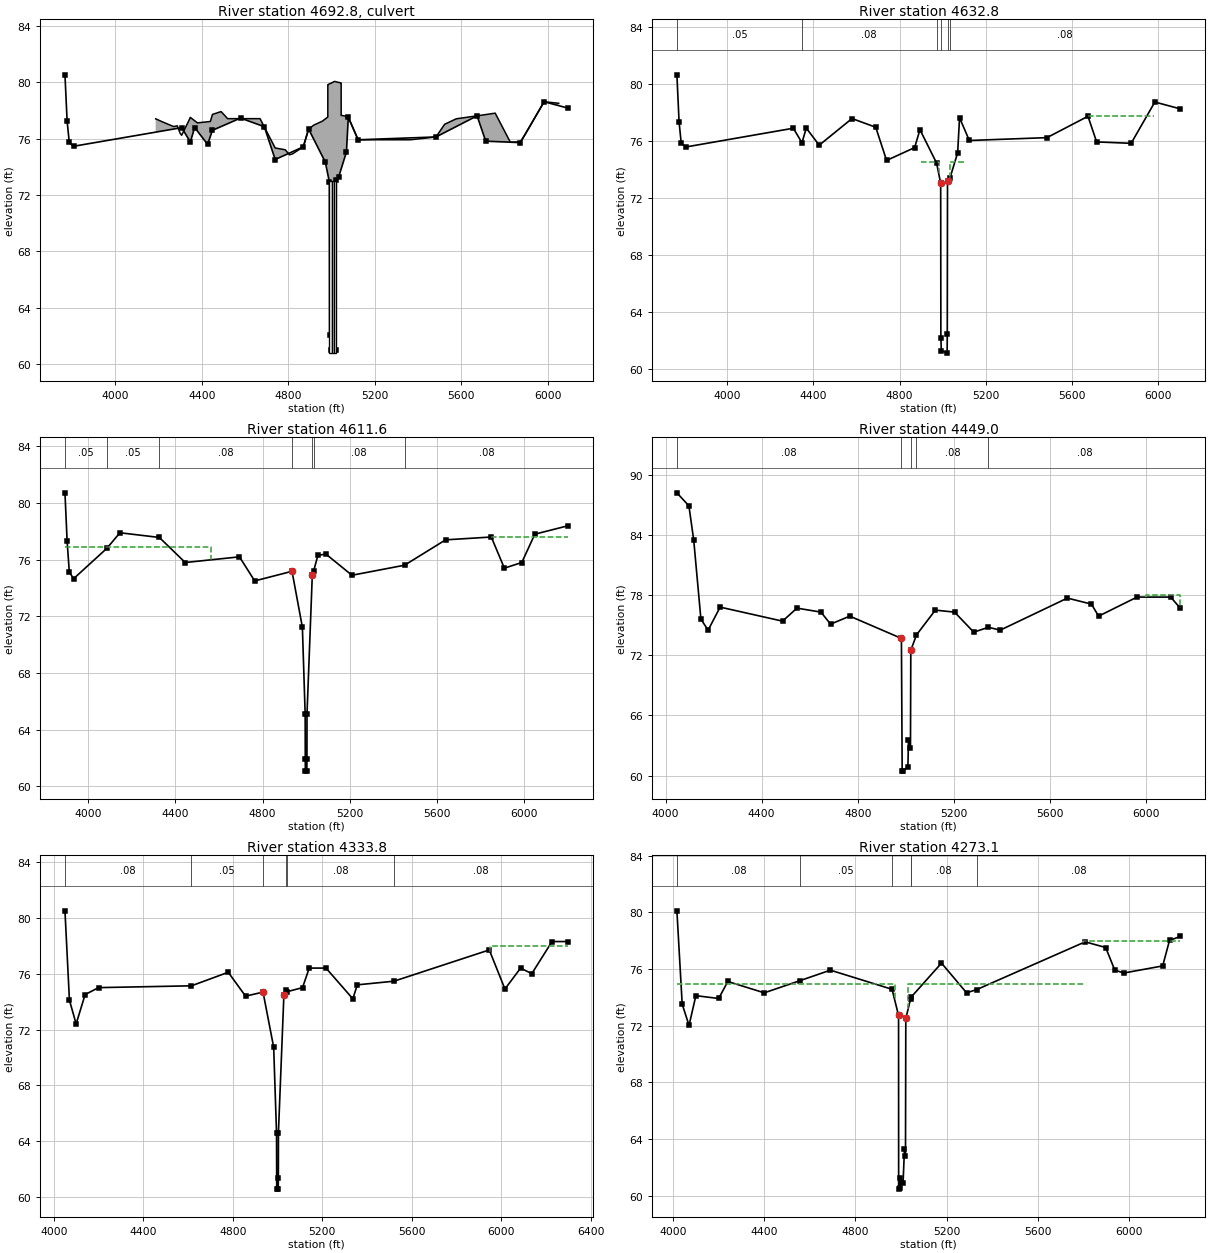
Type RM Length L Ch R = 2 ,4692.8  ,,,
BEGIN DESCRIPTION:
LANG ROAD
Structure ID: E115-04-00-3
END DESCRIPTION:
Bridge Culvert--1,0,-1,-1, 0
Deck Dist Width WeirC Skew NumUp NumDn MinLoCord MaxHiCord MaxSubmerge Is_Ogee
10,100,2.6,0, 88, 88, , , 0.95, 0, ,,,
  4187.1  4217.1    4270  4287.1    4290    4300  4307.1    4340  4340.8  4347.1
    4360    4370    4380    4440  4447.1  4449.7  4467.1  4487.1  4489.7  4501.7
  4506.2  4519.7  4669.7  4739.7  4786.2  4806.2  4811.7  4819.7  4869.7  4886.2
  4894.3    4918  4954.6  4958.6  4962.6  4971.6  4976.4  4981.7  4982.9 4982.99
  4983.1 4983.21  4984.1  4990.3  4990.4  4991.3  4992.1  4993.4  4995.6  4999.4
  5003.3  5007.9  5009.6  5014.1  5018.2    5021  5022.1  5030.1  5033.7  5035.1
  5042.8 5044.59  5044.7 5044.81  5049.5  5065.5  5069.2  5077.8    5117  5123.2
    5137  5363.2  5377.4  5483.2    5497  5523.2    5577  5673.2  5713.2    5757
    5827  5873.2    5897    5917    5947  5983.2  5984.5  6050.7
    77.4   77.19   76.85    76.9   76.78   76.38   76.23   77.25   77.28    77.5
   77.35   77.23   77.11   77.21   77.58   77.71    77.8    77.9   77.91   77.71
   77.64   77.41   77.41   75.33    75.2   74.84   74.87   74.91   75.41   76.26
   76.67   76.95   77.21   77.24   77.29   77.39   77.45   77.51   77.52   77.52
   79.82   79.82   79.83   79.87   79.87   79.88   79.89    79.9   79.91   79.94
   79.97      80   80.02   80.05   80.04   80.03   80.02   79.99   79.98   79.98
   79.95   79.94   79.94   77.64   77.63   77.59   77.45   77.51   76.13   75.91
   75.91   75.91   75.93   76.11   76.42   77.01    77.4   77.61    77.7    77.8
   75.74   75.76   76.34   76.86   77.66   78.61   78.61    78.5
                                                                                
                                                                                
                                                                                
                                                                                
                                                                                
                                                                                
                                                                                
                                                                                
                                                                
  4187.1  4217.1    4270  4287.1    4290    4300  4307.1    4340  4340.8  4347.1
    4360    4370    4380    4440  4447.1  4449.7  4467.1  4487.1  4489.7  4501.7
  4506.2  4519.7  4669.7  4739.7  4786.2  4806.2  4811.7  4819.7  4869.7  4886.2
  4894.3    4918  4954.6  4958.6  4962.6  4971.6  4976.4  4981.7  4982.9 4982.99
  4983.1 4983.21  4984.1  4990.3  4990.4  4991.3  4992.1  4993.4  4995.6  4999.4
  5003.3  5007.9  5009.6  5014.1  5018.2    5021  5022.1  5030.1  5033.7  5035.1
  5042.8 5044.59  5044.7 5044.81  5049.5  5065.5  5069.2  5077.8    5117  5123.2
    5137  5363.2  5377.4  5483.2    5497  5523.2    5577  5673.2  5713.2    5757
    5827  5873.2    5897    5917    5947  5983.2  5984.5  6050.7
    77.4   77.19   76.85    76.9   76.78   76.38   76.23   77.25   77.28    77.5
   77.35   77.23   77.11   77.21   77.58   77.71    77.8    77.9   77.91   77.71
   77.64   77.41   77.41   75.33    75.2   74.84   74.87   74.91   75.41   76.26
   76.67   76.95   77.21   77.24   77.29   77.39   77.45   77.51   77.52   77.52
   79.82   79.82   79.83   79.87   79.87   79.88   79.89    79.9   79.91   79.94
   79.97      80   80.02   80.05   80.04   80.03   80.02   79.99   79.98   79.98
   79.95   79.94   79.94   77.64   77.63   77.59   77.45   77.51   76.13   75.91
   75.91   75.91   75.93   76.11   76.42   77.01    77.4   77.61    77.7    77.8
   75.74   75.76   76.34   76.86   77.66   78.61   78.61    78.5
                                                                                
                                                                                
                                                                                
                                                                                
                                                                                
                                                                                
                                                                                
                                                                                
                                                                
BR Coef= 1 , 0 , 0 ,1.25, 0 ,,,0.8,0,2,0,
WSPro=,,,, 1 ,,,, 0 ,,,, 0 ,,,,-1 ,-1 ,-1 , 0 , 0 , 0 , 0 , 0
Culvert=2,12.2,10,100,0.015,0.5,1,8,1,60.8,4995.6,60.76,4995.6,Culvert #1  , 0 ,10
Culvert Bottom n=0.015
Culvert=2,12.2,10,100,0.02,0.4,1,8,1,60.79,5006.3,60.55,5006.3,Culvert #2  , 0 ,10
Culvert Bottom n=0.02
Culvert=2,12.2,10,100,0.02,0.4,1,8,1,60.77,5016.9,60.76,5016.9,Culvert #3  , 0 ,10
Culvert Bottom n=0.02
BC Design=,, 0 ,, 0 ,,,,,,
BC HTab HWMax=80.52

Type RM Length L Ch R = 1 ,4632.8  ,14.2,21.2,22.4
BEGIN DESCRIPTION:
Downstream Section of Bridge/Culvert/Weir
END DESCRIPTION:
XS GIS Cut Line= 5
        3081969.      13868404.3      3081598.11     13867933.18
      3081608.07     13867398.11      3081608.06     13867305.43
  3080744.611768  13866614.60745
#Sta/Elev= 30
  3767.7   80.64  3777.7   77.35  3787.7   75.84  3807.7   75.57  4307.4   76.89
  4347.4   75.87  4367.4    76.9  4427.4    75.7  4579.4   77.57  4689.4   76.96
  4739.7   74.63  4869.7   75.53  4894.3   76.79  4971.6   74.44  4990.4   73.02
  4991.3   62.18  4993.4   61.28 5020.34    61.1    5021   62.43  5022.1   73.18
  5033.7   73.41  5069.2   75.17  5077.8   77.63  5123.2   76.03  5483.2   76.23
  5673.2   77.73  5713.2   75.93  5873.2   75.83  5983.2   78.73  6100.9   78.25
#Mann= 6 ,-1 , 0
  3767.7     .05       0  4347.4     .08       0  4971.6     .04       0
  4990.4    .015       0  5022.1     .04       0  5033.7     .08       0
#XS Ineff= 4 ,-1
  3767.7    4575   76.93 4901.08  4980.4   74.49  5032.1 5107.72   74.49
 5673.44 5978.32   77.74
Permanent Ineff=
       F       F       F       F
Bank Sta=4990.4,5022.1
Exp/Cntr=0.5,0.3

Type RM Length L Ch R = 1 ,4611.6  ,405.6,162.6,56.3
BEGIN DESCRIPTION:
Cross Section X03.55 **See Note**
Concrete n-value in channel raised from 0.015 to 0.02 to account for bend losses.
END DESCRIPTION:
XS GIS Cut Line= 5
        3082042.       13868337.      3081889.21     13868165.61
      3081614.01      13867860.2       3081624.8     13867303.61
   3080766.29694  13866592.92228
#Sta/Elev= 30
  3892.3   80.72  3902.3   77.29  3912.3   75.12  3932.3   74.66  4084.7    76.8
  4144.7    77.9  4325.7   77.57  4444.7    75.8  4693.8    76.2  4763.8    74.5
  4935.2   75.18  4982.8   71.23  4995.6   65.07  4996.1   61.91  4996.4   61.07
  5003.1   61.09  5003.8    61.9    5004    65.1  5028.4   74.94  5034.1   75.17
  5053.8    76.3  5090.5    76.4  5210.5    74.9  5452.3   75.61  5640.5    77.4
  5850.5    77.6  5910.5    75.4  5990.5    75.8  6050.5    77.8  6204.2    78.4
#Mann= 7 ,-1 , 0
  3892.3     .05       0  4084.7     .05       0  4325.7     .08       0
  4935.2     .02       0  5028.4     .04       0  5034.1     .08       0
  5452.3     .08       0
#XS Ineff= 2 , 0
       0    4565    76.9 5849.59       0   77.61
Permanent Ineff=
       F       F
Bank Sta=4935.2,5028.4
Exp/Cntr=0.3,0.1

Type RM Length L Ch R = 1 ,4449.0  ,265.3,115.2,13.3
BEGIN DESCRIPTION:
Cross Section BR 3-US
END DESCRIPTION:
XS GIS Cut Line= 3
      3082437.15      13868070.7      3081704.94      13867295.4
      3080896.84      13866656.7
#Sta/Elev= 30
    4047    88.2    4097    86.9    4117    83.5    4147    75.6    4177    74.5
    4227    76.8    4487    75.4    4547    76.7    4647    76.3    4687    75.1
    4767    75.9  4982.1   73.68  4985.2   60.48  4989.8   60.44  5009.1   60.85
  5011.5   63.52  5019.8   62.76  5021.2   72.49  5044.9   74.03  5123.4    76.5
  5203.4    76.3  5283.4    74.3  5344.6   74.79  5393.4    74.5  5673.4    77.7
  5773.4    77.1  5803.4    75.9  5963.4    77.8  6103.4    77.8  6143.4    76.7
#Mann= 5 ,-1 , 0
    4047     .08       0  4982.1     .02       0  5021.2     .04       0
  5044.9     .08       0  5344.6     .08       0
#XS Ineff= 2 , 0
       0                    6000       0      78
Permanent Ineff=
       F       F
Bank Sta=4982.1,5021.2
Exp/Cntr=0.3,0.1

Type RM Length L Ch R = 1 ,4333.8  ,69.3,60.7,38
BEGIN DESCRIPTION:
Cross Section X03.5
END DESCRIPTION:
XS GIS Cut Line= 5
      3082650.73     13867745.27      3081995.73     13867288.89
      3081841.97     13867284.47      3081706.23     13867280.76
 3080800.1537078 13866562.066302
#Sta/Elev= 30
  4049.7    80.5  4069.7    74.1  4099.7    72.4  4139.7    74.5  4199.7      75
  4615.2   75.13  4779.7    76.1  4857.1   74.39  4935.2   74.68  4982.8   70.73
  4995.6   64.57  4996.4   60.57  5003.1   60.59  5003.8    61.4    5004    64.6
  5028.4   74.44  5038.4   74.85    5043   74.71  5111.8      75  5141.8    76.4
  5216.7    76.4  5336.7    74.2  5356.7    75.2  5520.5   75.46  5946.7    77.7
  6016.7    74.9  6086.7    76.4  6136.7      76  6227.2    78.3    6300    78.3
#Mann= 6 ,-1 , 0
  4049.7     .08       0  4615.2     .05       0  4935.2     .02       0
  5038.4     .04       0    5043     .08       0  5520.5     .08       0
#XS Ineff= 2 , 0
       0                    5950       0      78
Permanent Ineff=
       F       F
Bank Sta=4935.2,5028.4
Exp/Cntr=0.5,0.3

Type RM Length L Ch R = 1 ,4273.1  ,57,120,88.6
BEGIN DESCRIPTION:
Upstream Section of Bridge/Culvert/Weir **See Note**
Concrete n-value in channel raised from 0.015 to 0.02 to account for bend losses. --KHH
END DESCRIPTION:
XS GIS Cut Line= 5
      3082697.89     13867672.99      3082008.96     13867224.08
      3081837.86     13867219.45      3081664.28     13867212.22
  3080870.134638  13866540.27515
#Sta/Elev= 30
  4017.3   80.11  4040.5   73.52  4070.5   72.02  4100.5   74.12  4200.5   73.92
  4240.5   75.12  4400.5   74.32  4556.9   75.18  4690.5   75.92  4960.8   74.57
  4989.4   72.72  4989.8   60.46  4996.3   60.53  4996.8   61.25  5009.1   60.87
  5015.2   63.28  5019.8   62.78  5021.2   72.51  5042.3   73.91  5044.2   74.01
  5177.7   76.42  5287.7   74.32  5332.1   74.55  5807.7   77.92  5897.7   77.52
  5937.7   75.92  5977.7   75.72  6147.7   76.22  6177.7   78.02 6224.75    78.3
#Mann= 6 ,-1 , 0
  4017.3     .08       0  4556.9     .05       0  4960.8     .02       0
  5042.3     .04       0  5044.2     .08       0  5332.1     .08       0
#XS Ineff= 3 ,-1
  4017.3  4972.8   74.92  5031.2    5800   74.92    5800 6224.75      78
Permanent Ineff=
       F       F       F
Bank Sta=4989.4,5021.2
Exp/Cntr=0.5,0.3

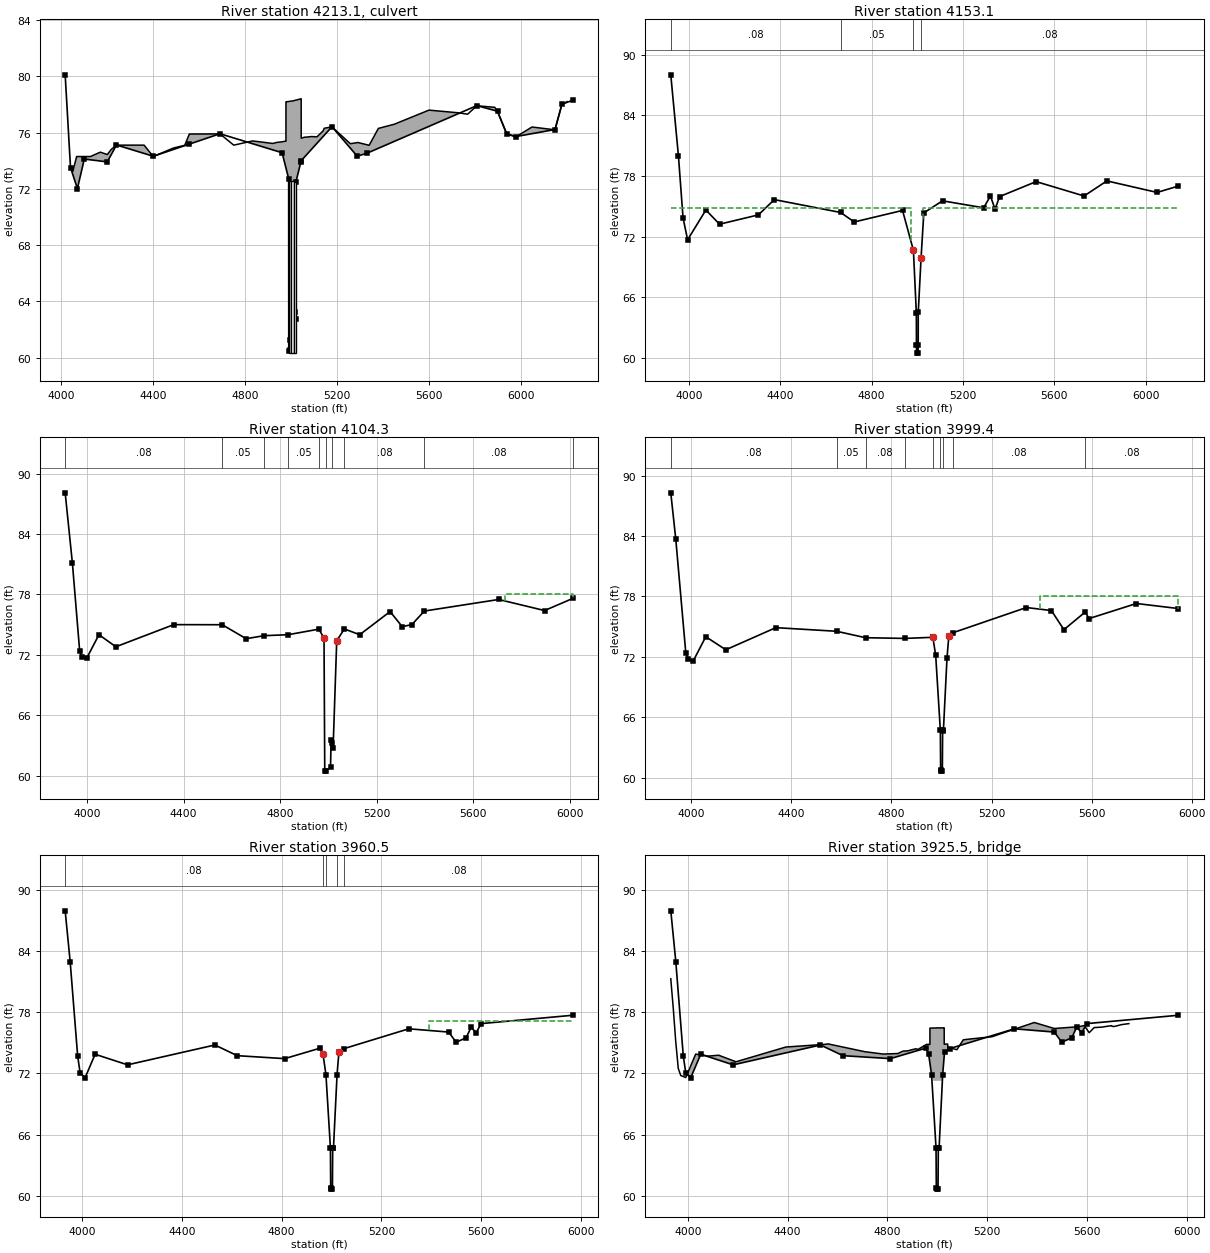
Type RM Length L Ch R = 2 ,4213.1  ,,,
BEGIN DESCRIPTION:
WEST 43RD STREET
Structure ID: E115-04-00-02
END DESCRIPTION:
Bridge Culvert--1,0,-1,-1, 0
Deck Dist Width WeirC Skew NumUp NumDn MinLoCord MaxHiCord MaxSubmerge Is_Ogee
10,100,2.6,0, 87, 87, , , 0.95, 0, ,,,
  4040.5  4050.5  4067.3  4070.5  4080.5  4100.5  4127.3  4157.3  4170.5  4200.5
  4217.3  4240.5  4327.3  4360.5  4400.5  4487.3  4537.3  4556.9  4557.3  4690.5
  4747.3  4750.5  4767.3  4832.8  4837.3  4861.8  4919.9    4920  4936.7  4942.1
  4960.8  4975.3 4977.49  4977.6 4977.71  4982.1  4989.4  4989.8    4991  4996.3
  4996.8  5000.5  5004.7    5007  5009.1  5015.1  5015.2  5019.8  5021.2  5034.8
  5042.3 5043.59  5043.8 5043.91  5044.2  5053.5  5056.9    5072  5082.1  5087.2
  5103.9  5112.4  5139.5  5143.9  5177.7  5199.5  5257.7  5287.7  5289.5  5332.1
  5339.5  5379.5  5449.5  5477.7  5599.5  5727.7  5739.5  5767.7  5807.7    5886
  5897.7  5937.7  5977.7  6047.7  6147.7  6177.7  6199.8
   73.51   73.25    74.3    74.3    74.3    74.3    74.3   74.52   74.61   74.44
    74.8   75.11   75.11   75.11    74.3    74.9    75.1   75.88    75.9   75.91
   75.15   75.11   75.17   75.41    75.4   75.35   75.23   75.23    75.3   75.31
   75.35   75.39   75.39   78.19   78.19    78.2   78.21   78.21   78.22   78.23
   78.23   78.24   78.25   78.25   78.26   78.29   78.29   78.31   78.31   78.37
    78.4   78.41   78.41   75.61   75.61   75.65   75.67   75.69   75.71   75.72
   75.71    75.7   76.13   76.31   76.41   76.08   75.21   75.29    75.3   75.13
    75.1    76.3    76.6   76.79    77.6   77.41   77.38   77.31   77.91    77.8
    77.5    75.9    75.7    76.4    76.2      78    78.2
                                                                                
                                                                                
                                                                                
                                                                                
                                                                                
                                                                                
                                                                                
                                                                                
                                                        
  4040.5  4050.5  4067.3  4070.5  4080.5  4100.5  4127.3  4157.3  4170.5  4200.5
  4217.3  4240.5  4327.3  4360.5  4400.5  4487.3  4537.3  4556.9  4557.3  4690.5
  4747.3  4750.5  4767.3  4832.8  4837.3  4861.8  4919.9    4920  4936.7  4942.1
  4960.8  4975.3 4977.49  4977.6 4977.71  4982.1  4989.4  4989.8    4991  4996.3
  4996.8  5000.5  5004.7    5007  5009.1  5015.1  5015.2  5019.8  5021.2  5034.8
  5042.3 5043.59  5043.8 5043.91  5044.2  5053.5  5056.9    5072  5082.1  5087.2
  5103.9  5112.4  5139.5  5143.9  5177.7  5199.5  5257.7  5287.7  5289.5  5332.1
  5339.5  5379.5  5449.5  5477.7  5599.5  5727.7  5739.5  5767.7  5807.7    5886
  5897.7  5937.7  5977.7  6047.7  6147.7  6177.7  6199.8
   73.51   73.25    74.3    74.3    74.3    74.3    74.3   74.52   74.61   74.44
    74.8   75.11   75.11   75.11    74.3    74.9    75.1   75.88    75.9   75.91
   75.15   75.11   75.17   75.41    75.4   75.35   75.23   75.23    75.3   75.31
   75.35   75.39   75.39   78.19   78.19    78.2   78.21   78.21   78.22   78.23
   78.23   78.24   78.25   78.25   78.26   78.29   78.29   78.31   78.31   78.37
    78.4   78.41   78.41   75.61   75.61   75.65   75.67   75.69   75.71   75.72
   75.71    75.7   76.13   76.31   76.41   76.08   75.21   75.29    75.3   75.13
    75.1    76.3    76.6   76.79    77.6   77.41   77.38   77.31   77.91    77.8
    77.5    75.9    75.7    76.4    76.2      78    78.2
                                                                                
                                                                                
                                                                                
                                                                                
                                                                                
                                                                                
                                                                                
                                                                                
                                                        
BR Coef= 1 , 0 , 0 ,1.25, 0 ,,,0.8,0,2,0,
WSPro=,,,, 1 ,,,, 0 ,,,, 0 ,,,,-1 ,-1 ,-1 , 0 , 0 , 0 , 0 , 0
Culvert=2,12.2,10,100,0.015,0.5,1,8,1,60.35,4994.9,60.31,4994.9,Culvert #1  , 0 ,10
Culvert Bottom n=0.015
Culvert=2,12.2,10,100,0.02,0.4,1,8,1,60.36,5005.6,60.31,5005.6,Culvert #2  , 0 ,10
Culvert Bottom n=0.02
Culvert=2,12.2,10,100,0.02,0.4,1,8,1,60.32,5016.2,60.29,5016.2,Culvert #3  , 0 ,10
Culvert Bottom n=0.02
BR D #Sta/Elev= 52
    3920      88  3953.7   79.94  3963.7   76.47  3973.7   73.86  3983.7   72.42
  3993.7   71.69  4003.7   71.64  4013.7   72.02  4023.7   72.91  4063.7   74.55
  4073.7   74.63  4133.7   73.23  4283.7   74.13  4293.7   74.45  4303.7   74.15
  4373.7   75.66    4375   75.65  4433.7   75.08  4473.7   75.08  4513.7   74.63
  4553.7   75.31  4603.7   74.54  4663.7   74.39  4723.7   73.45  4857.1    74.3
  4908.2   73.86  4935.2   74.59  4982.8   70.64  4995.6   64.48  4996.1   61.32
  4996.4   60.48  4999.8    60.5  5003.1    60.5  5003.8   61.31    5004   64.51
  5016.4   69.93  5028.4   74.35  5034.8   74.52  5110.3   75.54  5280.3   75.18
  5290.3   74.85  5320.3   76.02  5330.3   75.62  5340.3   74.71  5350.3   75.13
  5360.3   75.96  5520.3   77.44  5730.3   76.02  5830.3   77.51  6040.3   77.07
  6050.3   76.37 6143.15      77
BR D #Mann= 4
    3920     .08  4663.7     .05  4982.8     .02  5016.4     .08
BR D Banks=4982.8,5016.4
BC Design=,, 0 ,, 0 ,,,,,,
BC HTab HWMax=80.11

Type RM Length L Ch R = 1 ,4153.1  ,11.2,48.8,166.7
BEGIN DESCRIPTION:
Downstream Section of Bridge/Culvert/Weir **See Note**
Concrete n-value in channel raised from 0.015 to 0.02 to account for bend losses. --KHH
END DESCRIPTION:
XS GIS Cut Line= 5
      3082785.47     13867647.16   3081938.21955     13867115.23
     3081856.764   13867107.5849   3081669.39222   13867102.6863
   3080937.85266   13866486.1007
#Sta/Elev= 30
    3920      88  3953.7   79.94  3973.7   73.86  3993.7   71.69  4073.7   74.63
  4133.7   73.23  4303.7   74.15  4373.7   75.66  4663.7   74.39  4723.7   73.45
  4935.2   74.59  4982.8   70.64  4995.6   64.48  4996.1   61.32  4996.4   60.48
  5003.1    60.5  5003.8   61.31    5004   64.51  5016.4   69.93  5028.4   74.35
  5110.3   75.54  5290.3   74.85  5320.3   76.02  5340.3   74.71  5360.3   75.96
  5520.3   77.44  5730.3   76.02  5830.3   77.51  6050.3   76.37 6143.15      77
#Mann= 4 ,-1 , 0
    3920     .08       0  4663.7     .05       0  4982.8     .02       0
  5016.4     .08       0
#XS Ineff= 2 , 0
       0  4972.8   74.79 5026.74       0   74.79
Permanent Ineff=
       F       F
Bank Sta=4982.8,5016.4
Exp/Cntr=0.5,0.3

Type RM Length L Ch R = 1 ,4104.3  ,16,104.9,225.4
BEGIN DESCRIPTION:
Cross Section BR 3-DS
END DESCRIPTION:
XS GIS Cut Line= 4
      3082795.39      13867637.2      3081962.55      13867119.7
      3081757.57      13866983.9      3081076.67      13866431.9
#Sta/Elev= 30
  3909.6    88.1  3939.6    81.1  3969.6    72.4  3979.6    71.8  3999.6    71.7
  4049.6      74  4119.6    72.8  4359.6      75  4560.4   74.99  4659.6    73.6
  4732.9    73.9  4833.7      74  4960.5   74.55  4982.1   73.68  4985.2   60.48
  4989.8   60.44  5009.1   60.85  5011.5   63.52  5015.2   63.26  5019.8   62.76
  5034.8    73.4  5066.4   74.57  5130.1      74    5256    76.3    5306    74.8
    5346      75  5397.8   76.35    5706    77.5    5896    76.4  6012.6    77.6
#Mann= 10 ,-1 , 0
  3909.6     .08       0  4560.4     .05       0  4732.9     .08       0
  4833.7     .05       0  4960.5     .04       0  4989.8     .02       0
  5015.2     .04       0  5066.4     .08       0  5397.8     .08       0
  6012.6      .2       0
#XS Ineff= 2 , 0
       0                    5730       0      78
Permanent Ineff=
       F       F
Bank Sta=4982.1,5034.8
Exp/Cntr=0.3,0.1

Type RM Length L Ch R = 1 ,3999.4  ,11.4,38.9,64.8
BEGIN DESCRIPTION:
Cross Section BR 2-US
END DESCRIPTION:
XS GIS Cut Line= 4
       3082805.3      13867627.3      3081984.37      13867113.7
      3081921.67      13866878.5       3081262.9      13866394.6
#Sta/Elev= 30
  3917.7    88.3  3937.7    83.7  3977.7    72.4  3987.7    71.8  4007.7    71.6
  4057.7      74  4137.7    72.7  4337.7    74.9  4580.6   74.54  4696.4    73.9
  4854.2   73.83  4965.2   73.94 4965.53   73.93 4976.83   72.14 4995.43   64.68
 4996.53   60.75 4999.73   60.64 5003.43   60.67 5004.53    64.7 5007.63   64.67
 5022.03   71.89 5029.43    74.1    5044   74.38  5339.4    76.9  5439.4    76.6
  5489.4    74.7    5575   76.46  5589.4    75.8  5779.4    77.3  5946.8    76.8
#Mann= 9 ,-1 , 0
  3917.7     .08       0  4580.6     .05       0  4696.4     .08       0
  4854.2     .05       0  4965.2     .04       0 4995.43     .02       0
 5004.53     .04       0    5044     .08       0    5575     .08       0
#XS Ineff= 2 , 0
       0                    5395       0      78
Permanent Ineff=
       F       F
Bank Sta=4965.53,5029.43
Exp/Cntr=0.5,0.3

Type RM Length L Ch R = 1 ,3960.5  ,52,70,106
BEGIN DESCRIPTION:
Upstream Section of Bridge/Culvert/Weir **See Note**
Channel n-value increased to account for area blocked by pipeline upstream.
Composite n-value of channel below low chord: 0.029
Area w/o obstruction: 193.42 sq ft
Wet Perim. w/o obstruction: 88.87 ft
Capacity:  576.6 cfs
Area with obstruction: 156.72 sq ft
Wet Perim. with obstruction: 140.2 ft
Capacity: 299.6 cfs
576.6/266.6 = 1.92
1.92 * .029 = .056
--KHH
END DESCRIPTION:
XS GIS Cut Line= 5
      3082810.75      13867616.6      3081994.29      13867107.6
       3081995.5      13866987.2      3081974.15      13866864.4
        3081334.      13866340.5
#Sta/Elev= 30
  3932.2   87.98  3952.2      83  3982.2   73.73  3992.2   72.05  4012.2   71.59
  4052.2   73.89  4182.2   72.85  4532.2    74.8  4622.2   73.75  4812.2   73.46
  4954.3   74.49  4965.5   73.93  4977.5   71.87  4995.4   64.68  4996.5   60.75
  4999.7   60.64  5003.4   60.67  5004.5    64.7  5007.6   64.67    5022   71.89
  5029.4    74.1  5049.6   74.44  5309.4   76.39  5469.4   76.07  5499.4   75.07
  5539.4   75.51  5559.4   76.55  5579.4   75.99  5599.4    76.9 5966.58   77.72
#Mann= 5 ,-1 , 0
  3932.2     .08       0  4965.5     .04       0  4977.5    .056       0
    5022     .04       0  5049.6     .08       0
#XS Ineff= 2 , 0
       0  4965.5   73.88 5389.97       0    77.2
Permanent Ineff=
       F       F
Bank Sta=4965.5,5029.4
Exp/Cntr=0.5,0.3

Type RM Length L Ch R = 3 ,3925.5  ,,,
BEGIN DESCRIPTION:
LOCKFIELD STREET
Structure ID: E115-04-00-01
END DESCRIPTION:
Bridge Culvert--1,0,-1,-1, 0
Deck Dist Width WeirC Skew NumUp NumDn MinLoCord MaxHiCord MaxSubmerge Is_Ogee
10,50,2.6,0, 91, 91, , , 0.95, 0, ,,,
  3932.1  3942.1  3952.1  3962.1  3972.1  3983.4  3992.1  4023.4  4032.1  4043.4
  4053.4  4063.4  4082.1  4122.1  4123.4  4193.4  4393.4  4553.4  4562.1  4712.1
  4723.4  4783.4  4842.1  4863.4  4883.4  4894.2  4904.6  4915.5  4922.6  4950.3
  4957.2  4965.5 4970.79  4970.9 4971.01  4976.8  4977.1 4977.41  4977.5  4984.7
  4991.9  4992.7  4995.4  4996.5  4999.7  5001.8  5003.4  5004.5  5007.6  5009.2
 5019.39  5019.5    5022 5027.99  5028.1 5028.21  5029.4  5037.6    5042  5043.4
  5048.6  5049.6  5053.4  5079.1  5104.6  5133.4  5139.3  5148.6  5178.6  5188.6
  5219.3  5238.6  5268.6  5288.6  5298.6  5389.3  5469.3  5519.3  5568.6  5589.3
  5609.3  5618.6  5629.3  5648.6  5658.6  5698.6    5699  5706.2  5718.6  5738.6
  5768.4
    81.3    78.4    75.1    72.5    71.8   71.69    71.6   73.41   73.91   73.86
   73.82   73.78   73.71   73.79    73.8   73.15    74.6   74.87   74.91   74.13
    74.1   73.91   73.96    74.2   74.23   74.31   74.37   74.43   74.36   74.76
   74.86   74.86   74.86   76.46   76.46   76.46   76.46   76.46   76.46   76.47
   76.47   76.47   76.47   76.48   76.48   76.48   76.48   76.48   76.48   76.48
   76.48   76.48   76.48   76.48   76.48   74.88   74.88   74.89   74.89   74.38
   74.45   74.45    74.5   74.34   75.31   75.39   75.41   75.43   75.51   75.53
   75.61   75.77   76.02   76.18   76.26   77.01   76.42   76.51    76.6   76.71
   76.01   76.24   76.51   76.54   76.55    76.7   76.67   76.61   76.67    76.8
    76.9
                                                                                
                                                                                
                                                                                
                                   71.28   71.28   71.28   71.28   71.28   71.28
   71.28   71.28   71.28   71.28   71.28   71.28   71.28   71.28   71.28   71.28
   71.28   71.28   71.28
                                                                                
                                                                                
                                                                                
        
  3932.1  3942.1  3952.1  3962.1  3972.1  3983.4  3992.1  4023.4  4032.1  4043.4
  4053.4  4063.4  4082.1  4122.1  4123.4  4193.4  4393.4  4553.4  4562.1  4712.1
  4723.4  4783.4  4842.1  4863.4  4883.4  4894.2  4904.6  4915.5  4922.6  4950.3
  4957.2  4965.5 4970.79  4970.9 4971.01  4976.8  4977.1 4977.41  4977.5  4984.7
  4991.9  4992.7  4995.4  4996.5  4999.7  5001.8  5003.4  5004.5  5007.6  5009.2
 5019.39  5019.5    5022 5027.99  5028.1 5028.21  5029.4  5037.6    5042  5043.4
  5048.6  5049.6  5053.4  5079.1  5104.6  5133.4  5139.3  5148.6  5178.6  5188.6
  5219.3  5238.6  5268.6  5288.6  5298.6  5389.3  5469.3  5519.3  5568.6  5589.3
  5609.3  5618.6  5629.3  5648.6  5658.6  5698.6    5699  5706.2  5718.6  5738.6
  5768.4
    81.3    78.4    75.1    72.5    71.8   71.69    71.6   73.41   73.91   73.86
   73.82   73.78   73.71   73.79    73.8   73.15    74.6   74.87   74.91   74.13
    74.1   73.91   73.96    74.2   74.23   74.31   74.37   74.43   74.36   74.76
   74.86   74.86   74.86   76.46   76.46   76.46   76.46   76.46   76.46   76.47
   76.47   76.47   76.47   76.48   76.48   76.48   76.48   76.48   76.48   76.48
   76.48   76.48   76.48   76.48   76.48   74.88   74.88   74.89   74.89   74.38
   74.45   74.45    74.5   74.34   75.31   75.39   75.41   75.43   75.51   75.53
   75.61   75.77   76.02   76.18   76.26   77.01   76.42   76.51    76.6   76.71
   76.01   76.24   76.51   76.54   76.55    76.7   76.67   76.61   76.67    76.8
    76.9
                                                                                
                                                                                
                                                                                
                                   71.28   71.28   71.28   71.28   71.28   71.28
   71.28   71.28   71.28   71.28   71.28   71.28   71.28   71.28   71.28   71.28
   71.28   71.28   71.28
                                                                                
                                                                                
                                                                                
        
BR Coef= 1 , 1 , 0 ,1.25, 0 ,,,0.8,0,2,0,
WSPro=,,,, 1 ,,,, 0 ,,,, 0 ,,,,-1 ,-1 ,-1 , 0 , 0 , 0 , 0 , 0
BC Design=,, 0 ,, 0 ,,,,,,
BC HTab HWMax=87.98

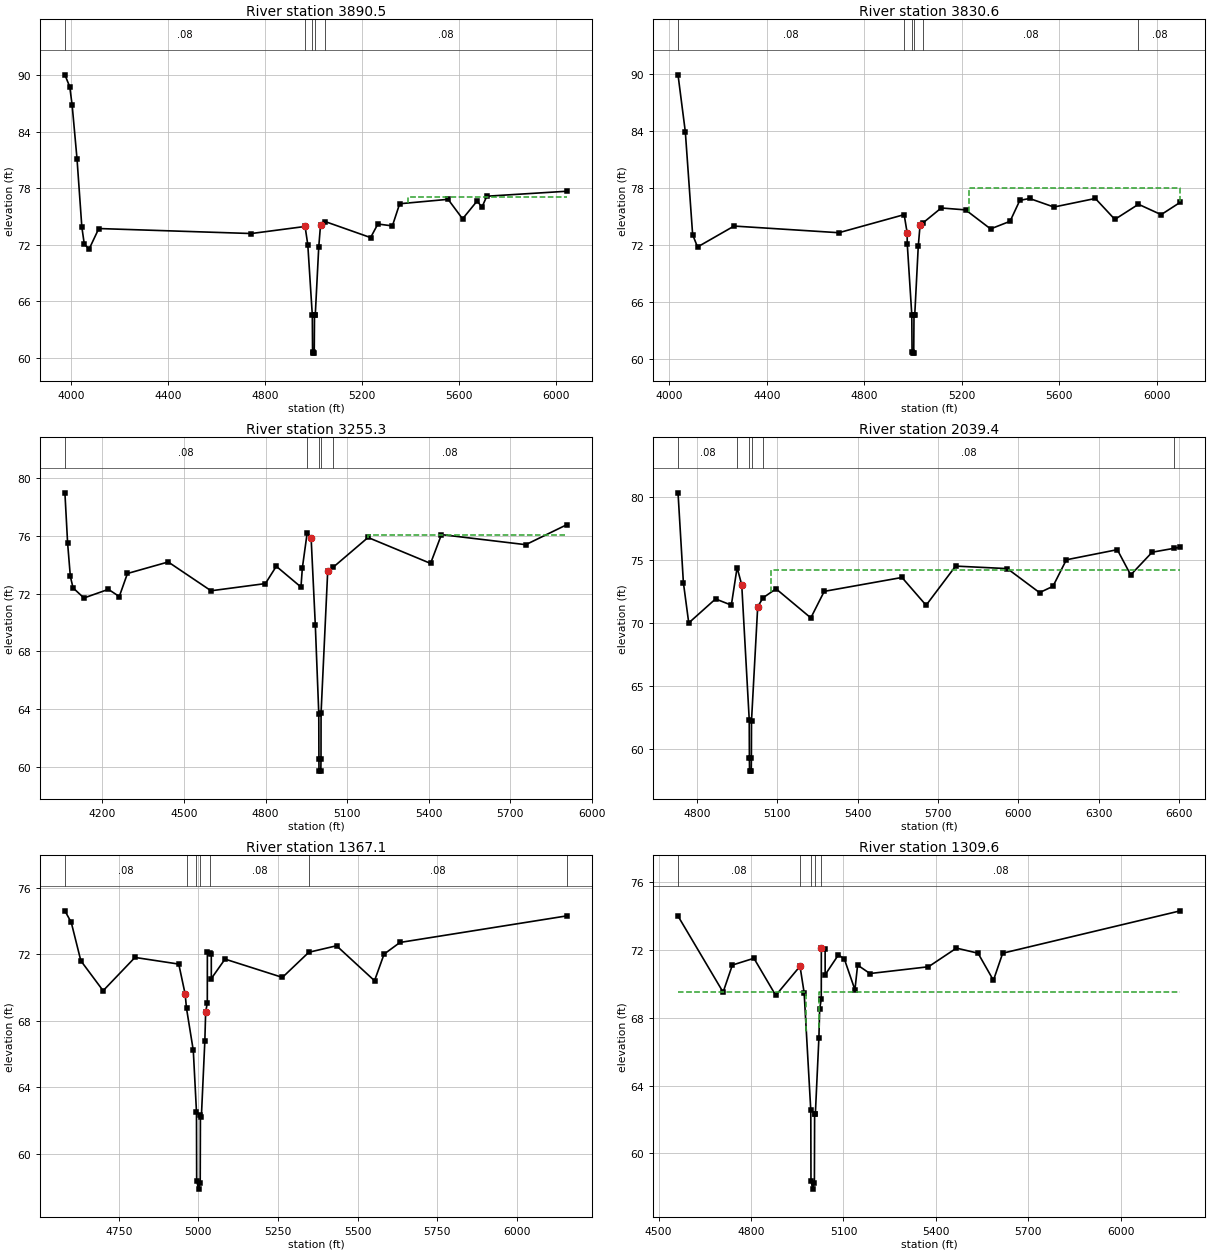
Type RM Length L Ch R = 1 ,3890.5  ,50,59.9,91
BEGIN DESCRIPTION:
Downstream Section of Bridge/Culvert/Weir
END DESCRIPTION:
XS GIS Cut Line= 5
      3082868.25      13867586.3      3082066.08      13867086.2
      3082067.16      13866979.9       3082038.3      13866811.2
  3081378.019834  13866272.78894
#Sta/Elev= 30
  3973.5   90.02  3993.5   88.75  4003.5   86.78  4023.5   81.11  4043.5   73.86
  4053.5   72.07  4073.5   71.53  4113.5   73.71  4743.5   73.18  4965.5   73.93
  4976.8   71.99  4995.4   64.53  4996.5    60.6  4999.7   60.49  5003.4   60.52
  5004.5   64.55  5007.6   64.52    5022   71.74  5029.4    74.1  5049.6   74.44
  5236.2   72.75  5266.2   74.19  5326.2   73.99  5356.2   76.34  5556.2   76.81
  5616.2   74.74  5676.2   76.63  5696.2   75.98  5716.2   77.14 6048.22   77.67
#Mann= 5 ,-1 , 0
  3973.5     .08       0  4965.5     .04       0  4995.4    .015       0
  5004.5     .04       0  5049.6     .08       0
#XS Ineff= 2 , 0
       0  4965.5    73.6 5389.97       0    77.1
Permanent Ineff=
       F       F
Bank Sta=4965.5,5029.4
Exp/Cntr=0.5,0.3

Type RM Length L Ch R = 1 ,3830.6  ,546,575.3,504
BEGIN DESCRIPTION:
Cross Section BR 2-DS
END DESCRIPTION:
XS GIS Cut Line= 4
      3082885.86      13867551.4      3082126.19      13867068.4
      3082106.09      13866756.6      3081438.97      13866232.1
#Sta/Elev= 30
  4036.1    89.9  4066.1    83.9  4096.1    73.1  4116.1    71.8  4266.1      74
  4696.1    73.3  4964.1    75.2  4976.3    73.3  4976.8   72.14  4995.4   64.68
  4996.5   60.75  4999.7   60.64  5003.4   60.67  5004.5    64.7  5007.6   64.67
    5022   71.89  5029.4    74.1  5042.6   74.36  5116.3    75.9  5216.3    75.7
  5318.7    73.7  5398.7    74.5  5438.7    76.7  5478.7    76.9  5578.7      76
  5748.7    76.9  5828.7    74.7  5925.6   76.29  6018.7    75.2  6097.3    76.5
#Mann= 6 ,-1 , 0
  4036.1     .08       0  4964.1     .04       0  4995.4    .015       0
  5004.5     .04       0  5042.6     .08       0  5925.6     .08       0
#XS Ineff= 2 , 0
       0                    5230       0      78
Permanent Ineff=
       F       F
Bank Sta=4976.3,5029.4
Exp/Cntr=0.3,0.1

Type RM Length L Ch R = 1 ,3255.3  ,905.7,1215.9,1168.3
BEGIN DESCRIPTION:
Cross Section X03
Located At: DS W 43RD
END DESCRIPTION:
XS GIS Cut Line= 5
      3082989.74      13867403.3      3082889.39      13866956.9
      3082528.53     13866644.32      3082167.91     13866342.74
      3081738.01      13866238.2
#Sta/Elev= 30
  4061.8      79  4071.8    75.5  4081.8    73.2  4091.8    72.4  4131.8    71.7
  4221.8    72.3  4261.8    71.8  4291.8    73.4  4441.8    74.2  4599.3    72.2
  4799.3    72.7  4839.3    73.9  4930.1   72.46  4935.2   73.79    4953   76.23
  4967.5   75.84  4982.8   69.84  4995.6   63.68  4996.1   60.52  4996.4   59.68
  5003.1    59.7  5003.8   60.51    5004   63.71  5028.4   73.55    5049   73.84
  5176.8    75.9  5406.8    74.1  5446.8    76.1  5756.9    75.4  5909.3    76.8
#Mann= 5 ,-1 , 0
  4061.8     .08       0    4953     .04       0  4995.6    .015       0
    5004     .04       0    5049     .08       0
#XS Ineff= 2 , 0
       0                 5176.15       0   76.05
Permanent Ineff=
       F       F
Bank Sta=4967.5,5028.4
Exp/Cntr=0.3,0.1

Type RM Length L Ch R = 1 ,2039.4  ,597,672.3,674
BEGIN DESCRIPTION:
Cross Section X02;
END DESCRIPTION:
XS GIS Cut Line= 6
      3083729.95     13866661.25      3083624.03     13866546.12
      3083633.44     13866441.03      3083641.48     13866331.64
      3083163.68     13865871.69      3082346.79      13866044.6
#Sta/Elev= 30
  4730.1    80.3  4750.1    73.2  4770.1      70  4870.1    71.9    4929   71.41
  4950.5   74.38  4967.8   73.01  4995.7   62.35  4996.3    59.3  4996.9   58.27
  5003.3   58.27  5003.8    59.3  5004.2   62.25  5027.3   71.27    5047   71.99
  5095.8    72.7  5225.5    70.4  5275.5    72.5  5565.5    73.6  5655.5    71.4
  5765.5    74.5  5958.7    74.3  6078.7    72.4  6128.7    72.9  6178.7      75
  6368.7    75.8  6418.7    73.8  6498.7    75.6  6580.9   75.91  6603.7      76
#Mann= 6 ,-1 , 0
  4730.1     .08       0  4950.5     .04       0  4995.7    .015       0
  5004.2     .04       0    5047     .08       0  6580.9     .05       0
#XS Ineff= 2 , 0
                         5075.88           74.16
Permanent Ineff=
       F       F
Bank Sta=4967.8,5027.3
Exp/Cntr=0.3,0.1

Type RM Length L Ch R = 1 ,1367.1  ,55.9,57.5,58.7
BEGIN DESCRIPTION:
Cross Section BR 1-US
END DESCRIPTION:
XS GIS Cut Line= 5
       3084055.5      13866400.5      3083995.52      13866048.1
      3083961.78      13865916.9      3083804.33       13865572.
      3083099.54       13865587.
#Sta/Elev= 30
  4580.8    74.6  4600.8    73.9  4630.8    71.6  4700.8    69.8  4800.8    71.8
  4938.3    71.4  4958.3    69.6  4962.6   68.74  4983.9   66.21  4993.9   62.52
  4994.5   58.38  5000.5   57.88  5005.6   58.27  5006.3   62.32  5009.3   62.24
  5020.2    66.8  5022.7   68.52  5027.9   69.07  5028.1   72.11  5035.9   72.06
  5040.4   72.03  5040.5   70.53  5083.5    71.7  5263.7    70.6  5346.6   72.11
  5433.7    72.5  5552.9    70.4  5582.9      72  5632.9    72.7  6157.8    74.3
#Mann= 7 ,-1 , 0
  4580.8     .08       0  4962.6     .04       0  4993.9    .015       0
  5006.3     .04       0  5035.9     .08       0  5346.6     .08       0
  6157.8      .2       0
Bank Sta=4958.3,5022.7
Exp/Cntr=0.5,0.3

Type RM Length L Ch R = 1 ,1309.6  ,53,53,53
BEGIN DESCRIPTION:
Upstream Section of Bridge/Culvert/Weir;
END DESCRIPTION:
XS GIS Cut Line= 5
      3084097.42     13866379.59      3084039.03     13866023.09
      3083998.04     13865865.23      3083825.54     13865525.81
      3083100.24      13865562.1
#Sta/Elev= 30
  4563.1      74  4709.4   69.51  4739.4   71.11  4809.4   71.51  4880.2   69.32
  4958.9   71.04  4972.3   69.48  4993.9   62.53  4994.5   58.39  5000.5   57.89
  5005.6   58.28  5006.3   62.33  5008.7   62.33  5020.2   66.81  5022.7   68.53
  5027.9   69.08  5028.1   72.12  5040.4   72.04  5040.5   70.54  5083.5   71.71
  5102.7   71.47  5137.1   69.65  5145.8   71.11  5185.8   70.61  5375.8   71.01
  5466.5   72.11  5536.5   71.81  5586.5   70.21  5616.5   71.81  6192.8   74.31
#Mann= 5 ,-1 , 0
  4563.1     .08       0  4958.9     .04       0  4993.9    .015       0
  5006.3     .04       0  5028.1     .08       0
#XS Ineff= 2 , 0
       0 4979.64    69.5 5021.03       0    69.5
Permanent Ineff=
       F       F
Bank Sta=4958.9,5028.1
Exp/Cntr=0.5,0.3