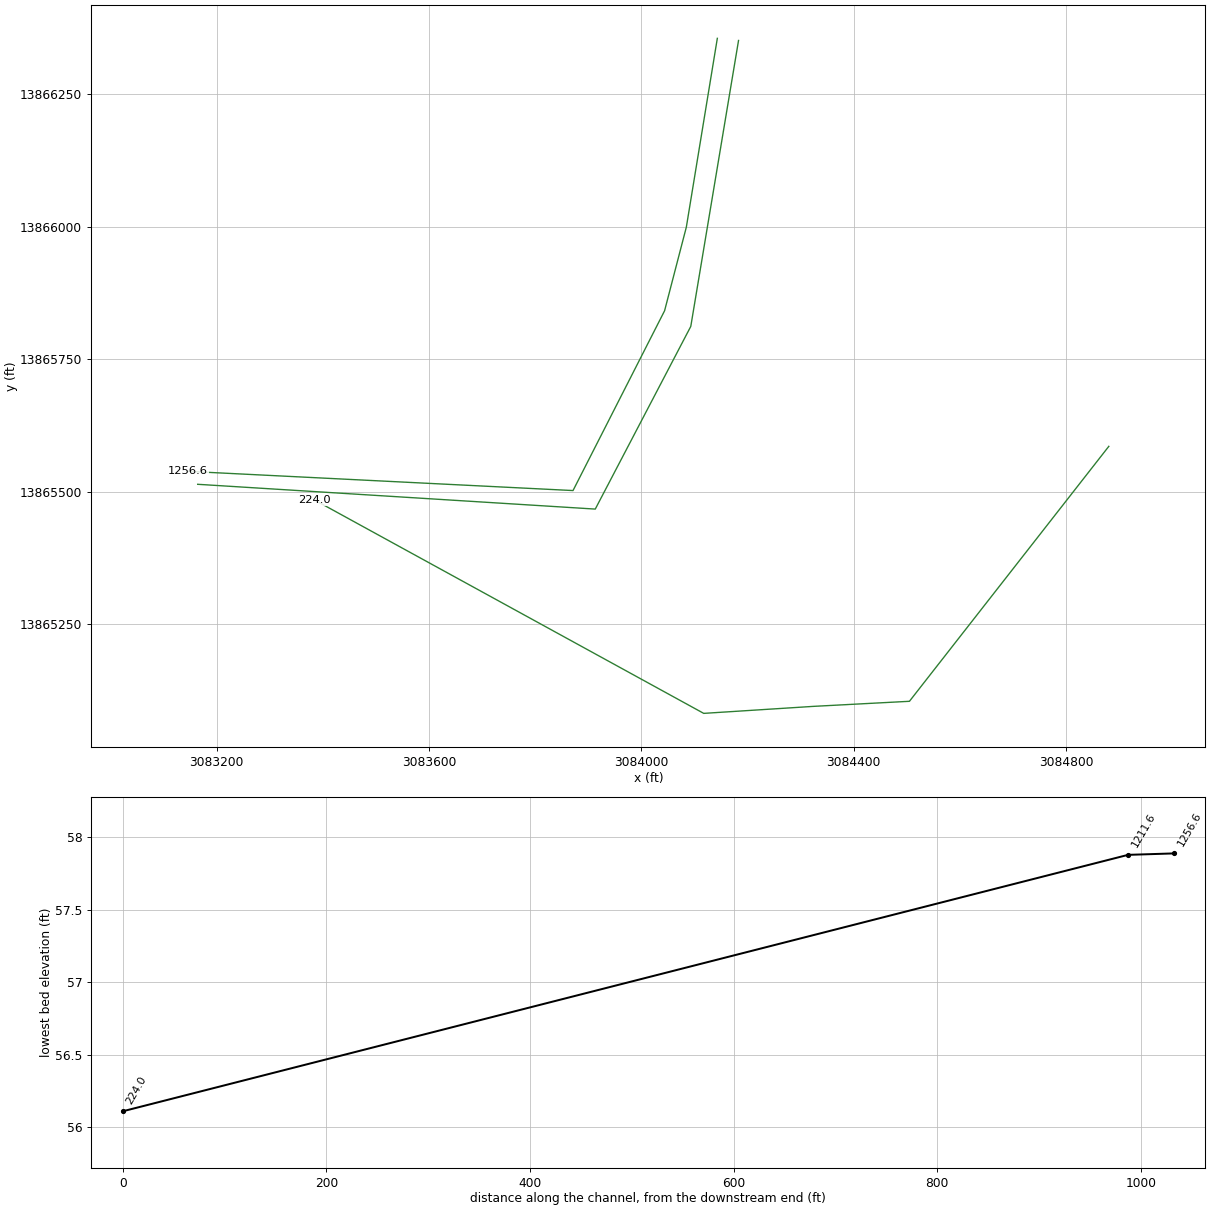
HEC-RAS study E115-04-00.prj: E115-04-00

--- E115-04-00.g01 (geometry) --- (continued)

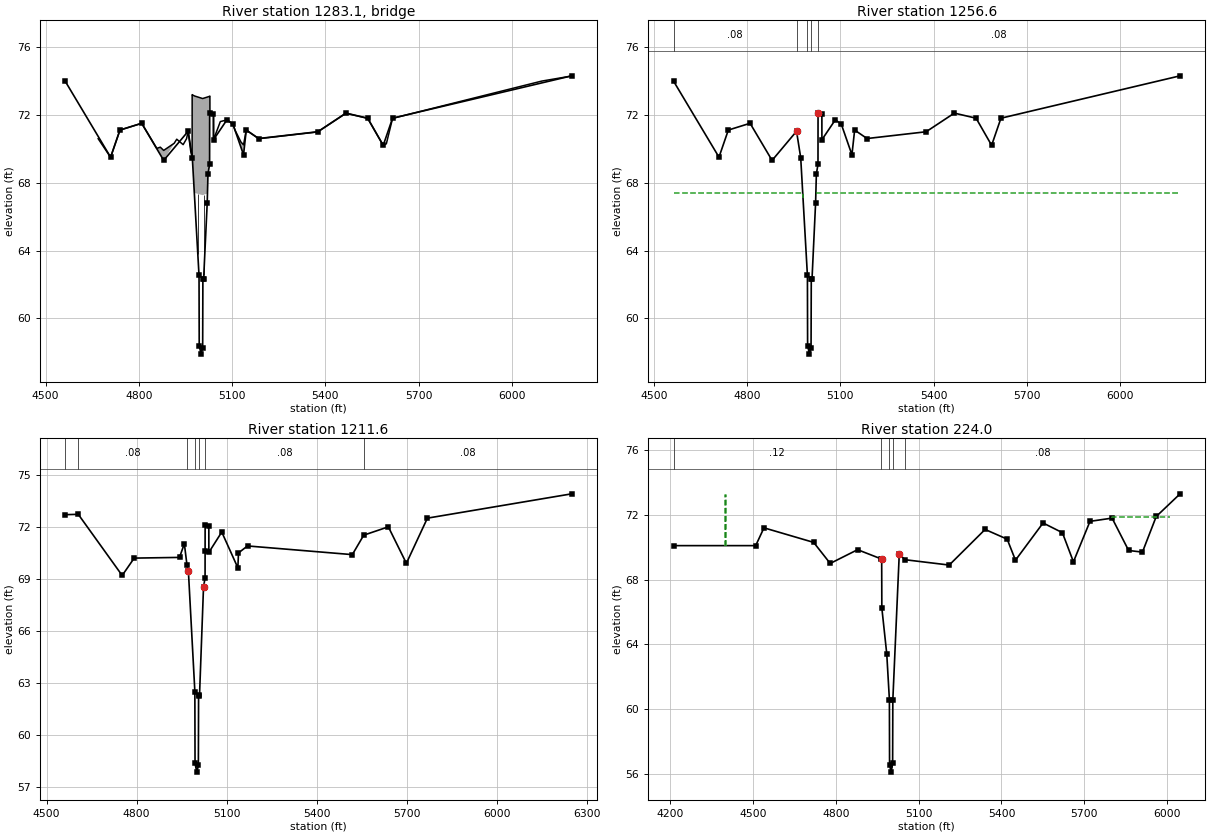
Type RM Length L Ch R = 3 ,1283.1  ,,,
BEGIN DESCRIPTION:
WOOD BRIDGE ACCESS RD 1280' U/S E115 CONFLUENCE
Structure ID: E115-04-00-S1A
END DESCRIPTION:
Bridge Culvert--1,0,-1,-1, 0
Deck Dist Width WeirC Skew NumUp NumDn MinLoCord MaxHiCord MaxSubmerge Is_Ogee
10,33,2.6,0, 43, 43, , , 0.95, 0, ,,,
  4669.4  4709.4  4739.4  4751.8  4809.4    4858  4869.3  4880.2    4914  4922.2
  4942.8  4953.8  4958.9  4967.4 4971.69  4971.8  4972.3 4979.67  5005.6 5021.03
  5022.7  5027.9  5028.1  5028.9 5029.01  5040.4  5040.5  5062.4  5083.5  5102.7
  5109.3  5128.9  5137.1  5145.8  5185.8  5375.8  5466.5  5536.5  5586.5  5596.5
  5616.5  6096.5  6192.8
    70.6    69.5    71.1   71.18   71.51   70.03    70.1   69.91   70.33   70.57
   70.25    70.6   71.04   69.83   69.52    73.2   73.19   73.12   72.97   73.06
   73.07    73.1   73.11   73.11   72.11   72.04   70.54   71.61   71.71   71.47
   71.12    70.4   70.24   71.11    70.6      71    72.1    71.8    70.2    70.3
    71.8      74    74.3
    70.6    69.5    71.1   71.17    71.5   70.02   69.66   69.31   70.32   70.56
   70.24   70.59   71.03   69.82   69.51   69.51   69.47    67.4   67.27   67.37
   68.52   69.07   72.11    72.1    72.1   72.03   70.53    71.6    71.7   71.46
   71.11   70.07   69.64    71.1    70.6      71    72.1    71.8    70.2    70.3
    71.8      74    74.3
  4669.4  4709.4  4739.4  4751.8  4809.4    4858  4869.3  4880.2    4914  4922.2
  4942.8  4953.8  4958.9  4967.4 4971.69  4971.8  4972.3 4979.67  5005.6 5021.03
  5022.7  5027.9  5028.1  5028.9 5029.01  5040.4  5040.5  5062.4  5083.5  5102.7
  5109.3  5128.9  5137.1  5145.8  5185.8  5375.8  5466.5  5536.5  5586.5  5596.5
  5616.5  6096.5  6192.8
    70.6    69.5    71.1   71.18   71.51   70.03    70.1   69.91   70.33   70.57
   70.25    70.6   71.04   69.83   69.52    73.2   73.19   73.12   72.97   73.06
   73.07    73.1   73.11   73.11   72.11   72.04   70.54   71.61   71.71   71.47
   71.12    70.4   70.24   71.11    70.6      71    72.1    71.8    70.2    70.3
    71.8      74    74.3
    70.6    69.5    71.1   71.17    71.5   70.02   69.66   69.31   70.32   70.56
   70.24   70.59   71.03   69.82   69.51   69.51   69.47    67.4   67.27   67.37
   68.52   69.07   72.11    72.1    72.1   72.03   70.53    71.6    71.7   71.46
   71.11   70.07   69.64    71.1    70.6      71    72.1    71.8    70.2    70.3
    71.8      74    74.3
Pier Skew, UpSta & Num, DnSta & Num=  ,4990, 2 ,4990, 2 , 0 , 0 , 0 ,,
       1       1
   62.37   68.35
       1       1
   66.32    72.3
Pier Skew, UpSta & Num, DnSta & Num=  ,5009.3, 2 ,5009.3, 2 , 0 , 0 , 0 ,,
       1       1
   61.36    68.3
       1       1
   65.31   72.25
BR Coef= 1 , 1 , 1 ,1.25, 0 ,,,0.8,0,2,0,
WSPro=,,,, 1 ,,,, 0 ,,,, 0 ,,,,-1 ,-1 ,-1 , 0 , 0 , 0 , 0 , 0
BC Design=,, 0 ,, 0 ,,,,,,
BC HTab HWMax=74.31

Type RM Length L Ch R = 1 ,1256.6  ,44,45,55
BEGIN DESCRIPTION:
Downstream Section of Bridge/Culvert/Weir
END DESCRIPTION:
XS GIS Cut Line= 5
        3084143.     13866355.75       3084084.6     13865999.25
      3084043.62     13865841.39      3083871.12     13865501.97
      3083145.81     13865538.26
#Sta/Elev= 30
  4563.1      74  4709.4   69.51  4739.4   71.11  4809.4   71.51  4880.2   69.32
  4958.9   71.04  4972.3   69.48  4993.9   62.53  4994.5   58.39  5000.5   57.89
  5005.6   58.28  5006.3   62.33  5008.7   62.33  5020.2   66.81  5022.7   68.53
  5027.9   69.08  5028.1   72.12  5040.4   72.04  5040.5   70.54  5083.5   71.71
  5102.7   71.47  5137.1   69.65  5145.8   71.11  5185.8   70.61  5375.8   71.01
  5466.5   72.11  5536.5   71.81  5586.5   70.21  5616.5   71.81  6192.8   74.31
#Mann= 5 ,-1 , 0
  4563.1     .08       0  4958.9     .04       0  4993.9    .015       0
  5006.3     .04       0  5028.1     .08       0
#XS Ineff= 2 , 0
       0 4979.76    67.4 5021.03       0    67.4
Permanent Ineff=
       F       F
Bank Sta=4958.9,5028.1
Exp/Cntr=0.5,0.3

Type RM Length L Ch R = 1 ,1211.6  ,1079.5,987.6,571
BEGIN DESCRIPTION:
Cross Section BR 1-DS
END DESCRIPTION:
XS GIS Cut Line= 4
      3084182.96      13866351.7      3084092.99      13865811.9
      3083913.04       13865467.      3083164.04      13865513.8
#Sta/Elev= 30
  4561.9    72.7  4605.7   72.72  4751.9    69.2  4791.9    70.2  4942.8   70.24
  4958.9   71.03  4967.6   69.81  4972.3   69.47  4993.9   62.52  4994.5   58.38
  5000.5   57.88  5005.6   58.27  5006.3   62.32  5009.3   62.24  5022.7   68.52
  5027.9   69.07    5028   70.59  5028.1   72.11  5040.4   72.03  5040.5   70.53
  5083.5    71.7  5137.1   69.64  5139.2    70.5  5169.2    70.9  5518.2    70.4
  5556.2   71.52  5638.2      72  5698.2    69.9  5768.2    72.5  6248.7    73.9
#Mann= 7 ,-1 , 0
  4561.9     .08       0  4605.7     .08       0  4967.6     .04       0
  4993.9    .015       0  5006.3     .04       0    5028     .08       0
  5556.2     .08       0
Bank Sta=4972.3,5022.7
Exp/Cntr=0.3,0.1

Type RM Length L Ch R = 1 ,224.0   ,0,0,0
BEGIN DESCRIPTION:
Cross Section XS01
Located At: DS LOCKFIELD ST
END DESCRIPTION:
XS GIS Cut Line= 5
   3084880.53034  13865585.45764       3084504.9     13865104.11
      3084324.61     13865094.57      3084117.38     13865081.31
       3083384.3     13865484.11
#Sta/Elev= 30
 4211.78    70.1  4509.5    70.1  4539.5    71.2  4719.5    70.3  4779.5      69
  4878.7   69.85  4964.2   69.28  4965.9   69.29  4966.5   66.25  4984.3   63.42
  4993.9   60.59  4994.5   56.55  5000.3   56.11  5005.6   56.66  5006.3   60.56
  5029.6   69.57  5050.7   69.23  5210.6    68.9  5340.6    71.1  5420.6    70.5
  5450.6    69.2  5550.6    71.5  5620.6    70.9  5660.6    69.1  5720.6    71.6
  5800.6    71.8  5860.6    69.8  5910.6    69.7  5960.6    71.9    6047    73.3
#Mann= 5 ,-1 , 0
 4211.78     .12       0  4964.2     .04       0  4993.9    .015       0
  5006.3     .04       0  5050.7     .08       0
#XS Ineff= 4 ,-1
  4399.5 4400.53   73.21
 5798.94 6010.12   71.85
Permanent Ineff=
       F       F       F       F
Bank Sta=4965.9,5029.6
Exp/Cntr=0.3,0.1

Chan Stop Cuts=-1
Use User Specified Reach Order=0
User Specified Reach Order=E115-04-00      ,E115-04-00_0002